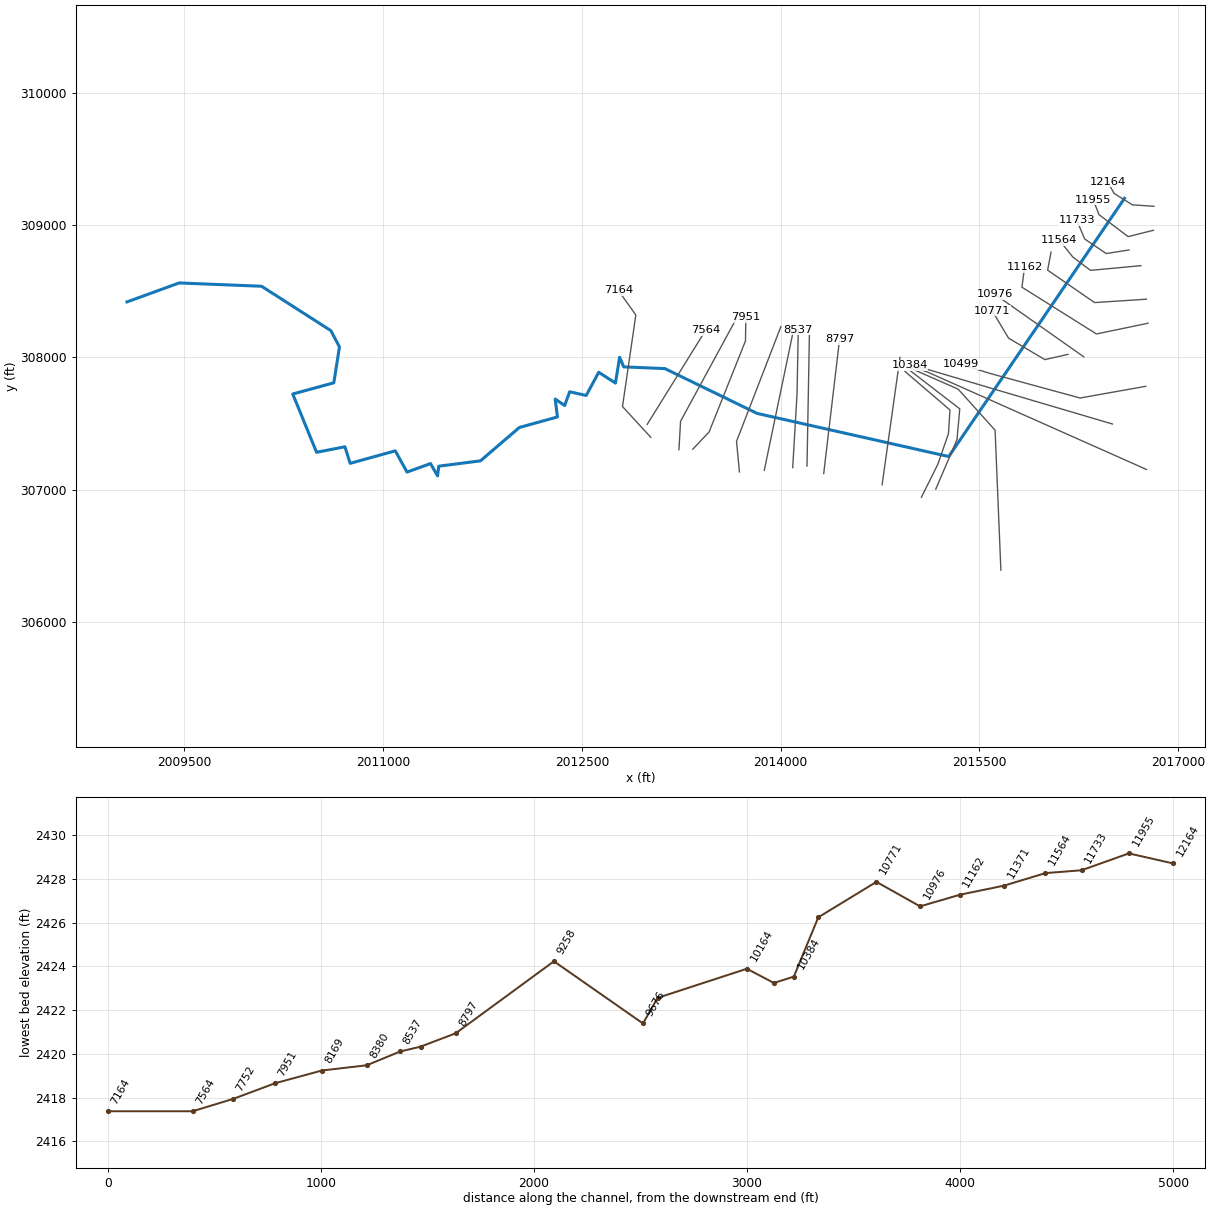
--- COONCK.prj (project) ---

Proj Title=COONCK
Current Plan=p01
Default Exp/Contr=0,0
English Units
Geom File=g01
Flow File=f01
Plan File=p01
BEGIN DESCRIPTION:
Stream Name: Coon Creek
Flood Zone: Approximate
Summers County, West Virginia
HEC-RAS Version: 5.0.7
Hydrology Method:
regression
Model Notes:
END DESCRIPTION:
DSS Export Rating Curves= 0
DSS Export Rating Curve Sorted= 0
DSS Export Volume Flow Curves= 0
DXF OffsetX= 0
DXF OffsetY= 0
DXF ScaleX= 0
DXF ScaleY= 0

--- COONCK.p01 (plan) ---

Plan Title=Floodplain
Program Version=5.07
Short Identifier=Floodplain
Geom File=g01
Flow File=f01
Subcritical Flow
K Sum by GR= 0
Std Step Tol= 0.01
Critical Tol= 0.01
Num of Std Step Trials= 20
Max Error Tol= 0.3
Flow Tol Ratio= 0.001
Split Flow NTrial= 30
Split Flow Tol= 0.02
Split Flow Ratio= 0.02
Log Output Level= 0
Friction Slope Method= 1
Unsteady Friction Slope Method= 2
Unsteady Bridges Friction Slope Method= 1
Parabolic Critical Depth
Global Vel Dist= 0 , 0 , 0
Global Log Level= 0
CheckData=True
Encroach Param=-1 ,0,0, 0
Mapping Interval=1HOUR
Computation Time Step Use Courant=        0
Computation Time Step Use Time Series=    0
Computation Time Step Count To Double=0
Computation Time Step Max Doubling=0
Computation Time Step Max Halving=0
Computation Time Step Residence Courant=0
Run HTab= 0
Run UNet= 0
Run Sediment= 0
Run PostProcess= 0
Run WQNet= 0
Run RASMapper= 0
UNET Theta= 0
UNET Theta Warmup= 0
UNET ZTol= 0
UNET ZSATol= 0
UNET MxIter= 0
UNET Max Iter WO Improvement= 0
UNET MaxInSteps= 0
UNET DtIC= 0
UNET DtMin= 0
UNET MaxCRTS= 0
UNET WFStab= 0
UNET SFStab= 0
UNET WFX= 1
UNET SFX= 1
UNET 1D Methodology=Finite Difference
UNET DSS MLevel= 1
UNET Pardiso=0
UNET DZMax Abort= 0
UNET Use Existing IB Tables= 0
UNET Froude Reduction=False
UNET Froude Limit= 0
UNET Froude Power= 0
UNET D1 Cores= 0
UNET D2 Coriolis=0
UNET D2 Cores= 0
UNET D2 Theta= 1
UNET D2 Theta Warmup= 1
UNET D2 Z Tol= 0.01
UNET D2 Volume Tol= 0.01
UNET D2 Max Iterations= 20
UNET D2 Equation= 0
UNET D2 RampUpFraction=0.1
UNET D2 TimeSlices= 1
UNET D2 BCVolumeCheck=0
UNET D1D2 MaxIter= 0
UNET D1D2 ZTol=0.01
UNET D1D2 QTol=0.1
UNET D1D2 MinQTol=1
Write IC File= 0
Write IC File at Fixed DateTime=0
Write IC File at Sim End=0
Echo Input=False
Echo Parameters=False
Echo Output=False
Write Detailed= 0
HDF Write Warmup=0
HDF Write Time Slices=0
HDF Flush=0
HDF Face Node Velocities=0
HDF Compression= 1
HDF Chunk Size= 1
HDF Spatial Parts= 1
HDF Use Max Rows=0
HDF Fixed Rows= 1
Calibration Method= 0
Calibration Iterations= 20
Calibration Max Change=0.05
Calibration Tolerance=0.2
Calibration Maximum=1.5
Calibration Minimum=0.5
Calibration Optimization Method= 1
WQ AD Non Conservative
WQ ULTIMATE=-1
WQ Max Comp Step=1HOUR
WQ Output Interval=15MIN
WQ Output Selected Increments= 0
WQ Output face flow=0
WQ Output face velocity=0
WQ Output face area=0
WQ Output face dispersion=0
WQ Output cell volume=0
WQ Output cell surface area=0
WQ Output cell continuity=0
WQ Output cumulative cell continuity=0
WQ Output face conc=0
WQ Output face dconc_dx=0
WQ Output face courant=0
WQ Output face peclet=0
WQ Output face adv mass=0
WQ Output face disp mass=0
WQ Output cell mass=0
WQ Output cell source sink temp=0
WQ Output nsm pathways=0
WQ Output nsm derived pathways=0
WQ Output MaxMinRange=-1
WQ Daily Max Min Mean=-1
WQ Daily Range=0
WQ Daily Time=0
WQ Create Restart=0
WQ Fixed Restart=0
WQ System Summary=0
WQ Write To DSS=0
WQ Use Fixed Temperature=0
Sorting and Armoring Iterations= 10
XS Update Threshold= 0.02
Bed Roughness Predictor= 0
Hydraulics Update Threshold= 0.02
Energy Slope Method= 1
Volume Change Method= 1
Sediment Retention Method= 0
XS Weighting Method= 0
Number of US Weighted Cross Sections= 1
Number of DS Weighted Cross Sections= 1
Upstream XS Weight=0
Main XS Weight=1
Downstream XS Weight=0
Number of DS XS's Weighted with US Boundary= 1
Upstream Boundary Weight= 1
Weight of XSs Associated with US Boundary= 0
Number of US XS's Weighted with DS Boundary= 1
Downstream Boundary Weight= 0.5
Weight of XSs Associated with DS Boundary= 0.5
Percentile Method= 0
Sediment Output Level= 3
Mass or Volume Output= 0
Output Increment Type= 1
Profile and TS Output Increment= 1
XS Output Flag= 0
XS Output Increment= 10
Write Gradation File= 0
Read Gradation Hotstart= 0
Write HDF5 File= 1
Write Binary Output= 1
Write DSS Sediment File= 0
SV Curve= 0
Specific Gage Flag= 0

--- COONCK.f01 (steady flow) ---

Flow Title=Flows
Program Version=5.07
Number of Profiles= 6
Profile Names=01pct,10pct,04pct,02pct,0_2pct,01plus
River Rch & RM=COONCK,Main            ,12164
     599     317     421     507     836     886
River Rch & RM=COONCK,Main            ,9258
     670     356     472     568     933     991
River Rch & RM=COONCK,Main            ,7752
     745     398     527     632    1036    1102
River Rch & RM=COONCK,Main            ,3828
     858     460     608     729    1189    1269
Boundary for River Rch & Prof#=COONCK,Main            , 1
Up Type= 0
Dn Type= 3
Dn Slope=0.125677
Boundary for River Rch & Prof#=COONCK,Main            , 2
Up Type= 0
Dn Type= 3
Dn Slope=0.125677
Boundary for River Rch & Prof#=COONCK,Main            , 3
Up Type= 0
Dn Type= 3
Dn Slope=0.125677
Boundary for River Rch & Prof#=COONCK,Main            , 4
Up Type= 0
Dn Type= 3
Dn Slope=0.125677
Boundary for River Rch & Prof#=COONCK,Main            , 5
Up Type= 0
Dn Type= 3
Dn Slope=0.125677
Boundary for River Rch & Prof#=COONCK,Main            , 6
Up Type= 0
Dn Type= 3
Dn Slope=0.125677
DSS Import GetInterval= 0
DSS Import GetPeak= 0
DSS Import FillOption= 0

--- COONCK.g01 (geometry) ---

Geom Title=Geometry
Program Version=5.07

River Reach=COONCK          ,Main
Reach XY= 30
     2016594.661309203.7859999142015268.28899999307250.580999915
     2013821.981307576.9099999132013125.79999999 307915.88599991
      2012815.47307928.9069999152012784.21999999308001.823999916
     2012752.967307806.575999914     2012626.578307887.825999915
2012532.13299999 307712.478999912012407.13299999307740.603999914
2012369.63299999 307636.437999912012298.10599999307685.395999914
     2012315.119307549.9789999082012027.81622006307470.448324784
     2011733.811307217.9159999132011419.40199999307177.637999913
2011410.02699999 307104.026999912011357.50899999307197.255999919
2011179.64499999307132.9329999132011091.36399999307293.610999907
2010750.47799999307199.0789999152010711.41599999 307324.33999991
     2010497.093 307282.672999912010317.36299999307723.587999913
2010627.31299999307808.3159999122010669.95699999308079.911999917
     2010604.853308203.1759999132010082.21519861 308538.71082794
2009460.25935935308563.898420068 2009066.5345801308420.423751885

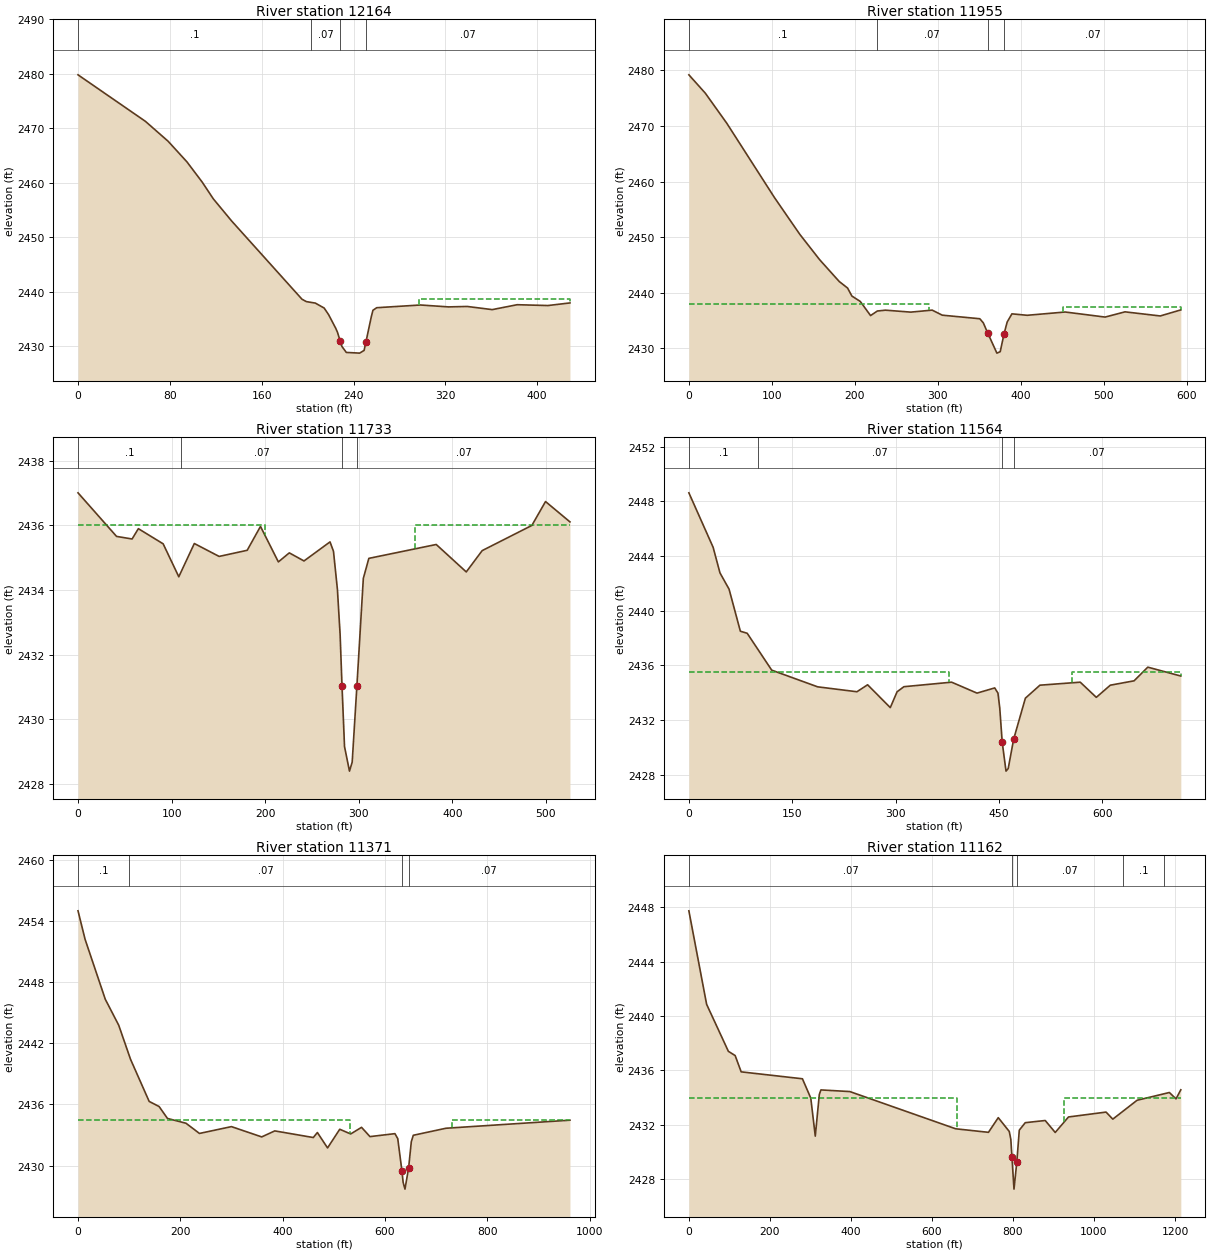
Type RM Length L Ch R = 1 ,12164   ,208.8,208.8,208.8
XS GIS Cut Line= 4
2016817.31400378309143.8038339552016654.74746666309154.626784908
2016516.29320419309241.0074359412016466.76547411309330.594056976
#Sta/Elev= 30
       0 2479.81    58.7 2471.27    78.5 2467.61    94.9 2463.82   108.1 2460.13
   117.9 2457.02   133.9 2452.95   195.1  2438.6   198.9 2438.16   206.7 2437.89
   214.4 2436.98   218.3 2435.76   224.5 2433.26     226 2432.53   228.52430.837
   229.9 2429.92   233.7 2428.83   245.3  2428.7   249.2  2429.2   250.7 2430.66
   255.5 2435.41   256.9 2436.57   260.2 2437.04   298.3 2437.54   322.7 2437.19
     339 2437.27   360.8 2436.69   382.5 2437.59   409.4 2437.44   428.5 2437.92
#Mann= 4 ,-1 , 0
       0      .1       0  202.93     .07       0   228.5    .045       0
   250.7     .07       0
#XS Ineff= 2 , 0
                          296.62         2438.62
Permanent Ineff=
       F       F
Bank Sta=228.5,250.7
XS Rating Curve= 0 ,0
Exp/Cntr=0.3,0.1

Type RM Length L Ch R = 1 ,11955   ,218.7,222,221
XS GIS Cut Line= 4
2016812.87317233308962.2861949632016622.40038364308914.218642773
2016401.88115528309081.1062591482016359.23177759309192.942441505
#Sta/Elev= 30
       0 2479.18    19.8 2475.88    45.7 2470.47   103.2  2457.1   133.7  2450.5
   157.4 2445.98   181.1 2442.04   191.2 2440.86   196.4 2439.42   206.5 2438.45
   218.9 2435.91   227.1 2436.73   236.9 2436.88   267.4 2436.53   293.1 2436.89
   305.3 2435.98   350.5 2435.34   354.7 2434.61   360.12432.761   371.1 2429.16
   375.1 2429.42   379.8 2432.68   383.5 2434.75   389.2 2436.22   407.6 2435.96
   453.4 2436.55   501.5 2435.64   525.5 2436.58   567.9 2435.84   592.7 2436.93
#Mann= 4 ,-1 , 0
       0      .1       0  226.44     .07       0   360.1    .045       0
   379.8     .07       0
#XS Ineff= 2 , 0
          289.46 2437.94  450.37         2437.49
Permanent Ineff=
       F       F
Bank Sta=360.1,379.8
XS Rating Curve= 0 ,0
Exp/Cntr=0.3,0.1

Type RM Length L Ch R = 1 ,11733   ,169.5,169.1,168.2
XS GIS Cut Line= 4
2016628.81497413308813.3368335482016457.01949211308786.116157132
2016294.36139847308896.3928307832016234.03613836309039.451413698
#Sta/Elev= 30
       0 2437.01    41.2 2435.66    57.8 2435.58    64.5  2435.9      91 2435.43
   107.7 2434.41   124.3 2435.44   150.8 2435.04   180.8 2435.23     195 2435.97
   214.1 2434.87   225.8 2435.15   241.5  2434.9   269.3 2435.49     273  2435.2
   277.2 2434.02   280.1 2432.62   282.12431.042   284.8 2429.15   290.1 2428.39
     293 2428.67     2982431.015   304.9 2434.36   310.8 2434.98   382.8 2435.41
   414.9 2434.56   431.9 2435.22     485    2436   499.6 2436.74   525.7 2436.11
#Mann= 4 ,-1 , 0
       0      .1       0     110     .07       0   282.1    .045       0
     298     .07       0
#XS Ineff= 2 , 0
             200    2436     360            2436
Permanent Ineff=
       F       F
Bank Sta=282.1,298
XS Rating Curve= 0 ,0
Exp/Cntr=0.3,0.1

Type RM Length L Ch R = 1 ,11564   ,190.6,193.2,192.8
XS GIS Cut Line= 4
2016718.29347624 308694.599514962016338.23895196308658.960256269
2016204.76160113 308759.925447142016102.18309363308888.733620548
#Sta/Elev= 30
       0 2448.63    35.2 2444.64    45.1 2442.77    58.3 2441.58    74.7  2438.5
    84.6 2438.35   120.2 2435.65   186.8 2434.43   243.8 2434.07   259.3 2434.58
   292.2 2432.91   302.1 2434.07     312 2434.44   381.2 2434.77     418 2433.97
   443.7 2434.35   448.4 2433.97     451 2432.89   454.6 2430.37   460.1 2428.26
   463.3 2428.45   471.22430.602   488.2  2433.6   509.3 2434.55   567.8 2434.77
   591.1 2433.66   611.4 2434.55   645.9 2434.87   665.8 2435.87   713.7 2435.22
#Mann= 4 ,-1 , 0
       0      .1       0     100     .07       0   454.6    .045       0
   471.2     .07       0
#XS Ineff= 2 , 0
             378  2435.5     556          2435.5
Permanent Ineff=
       F       F
Bank Sta=454.6,471.2
XS Rating Curve= 0 ,0
Exp/Cntr=0.3,0.1

Type RM Length L Ch R = 1 ,11371   ,207.6,208.8,208.3
XS GIS Cut Line= 4
2016759.39387463308440.7353858632016368.79815319308415.310841982
2016014.53433908308660.6764408552016040.65448355308797.413452967
#Sta/Elev= 30
       0 2454.98    13.8 2452.19    53.3 2446.31    79.6 2443.76   102.6 2440.43
   139.1 2436.29   158.5 2435.79   174.9 2434.62   211.1 2434.15   237.4 2433.15
   299.9 2433.82   359.1 2432.81   384.6  2433.4   459.9 2432.75   467.9 2433.24
   487.8 2431.73   511.6 2433.56     533  2433.1   554.2 2433.75   570.7 2432.84
   619.5 2433.13     625 2432.64   633.22429.467   635.5 2428.36   639.1 2427.69
   646.2 2429.75   651.5 2432.34   655.4 2432.97   719.3 2433.66   961.6 2434.45
#Mann= 4 ,-1 , 0
       0      .1       0     100     .07       0   633.2    .045       0
   646.2     .07       0
#XS Ineff= 2 , 0
             532  2434.5     732          2434.5
Permanent Ineff=
       F       F
Bank Sta=633.2,646.2
XS Rating Curve= 0 ,0
Exp/Cntr=0.3,0.1

Type RM Length L Ch R = 1 ,11162   ,184.6,186.3,185
XS GIS Cut Line= 4
2016772.08042331308259.049779573 2016383.3147842308177.815168415
2015820.47497833308531.7659741732015840.78363111308682.630252037
#Sta/Elev= 30
       0 2447.75    43.8 2440.87    97.5 2437.41   114.2  2437.1   129.1  2435.9
   280.3 2435.39   300.9 2433.97     312 2431.17     322 2434.24   325.9 2434.57
   397.2 2434.45   658.6 2431.71   739.5 2431.45   763.7 2432.53   790.9 2431.51
   794.7 2430.93   797.42429.656   802.5 2427.27   809.52429.271   815.6 2431.61
   830.3 2432.16   879.6 2432.32   904.3 2431.44     937 2432.58  1029.8 2432.94
  1046.4 2432.42  1106.4 2433.81  1186.1 2434.38  1202.4 2433.91  1214.3 2434.58
#Mann= 5 ,-1 , 0
       0     .07       0   797.4    .045       0   809.5     .07       0
 1072.05      .1       0 1172.05     .07       0
#XS Ineff= 2 , 0
             662    2434     926            2434
Permanent Ineff=
       F       F
Bank Sta=797.4,809.5
XS Rating Curve= 0 ,0
Exp/Cntr(USF)=0,0
Exp/Cntr=0.3,0.1

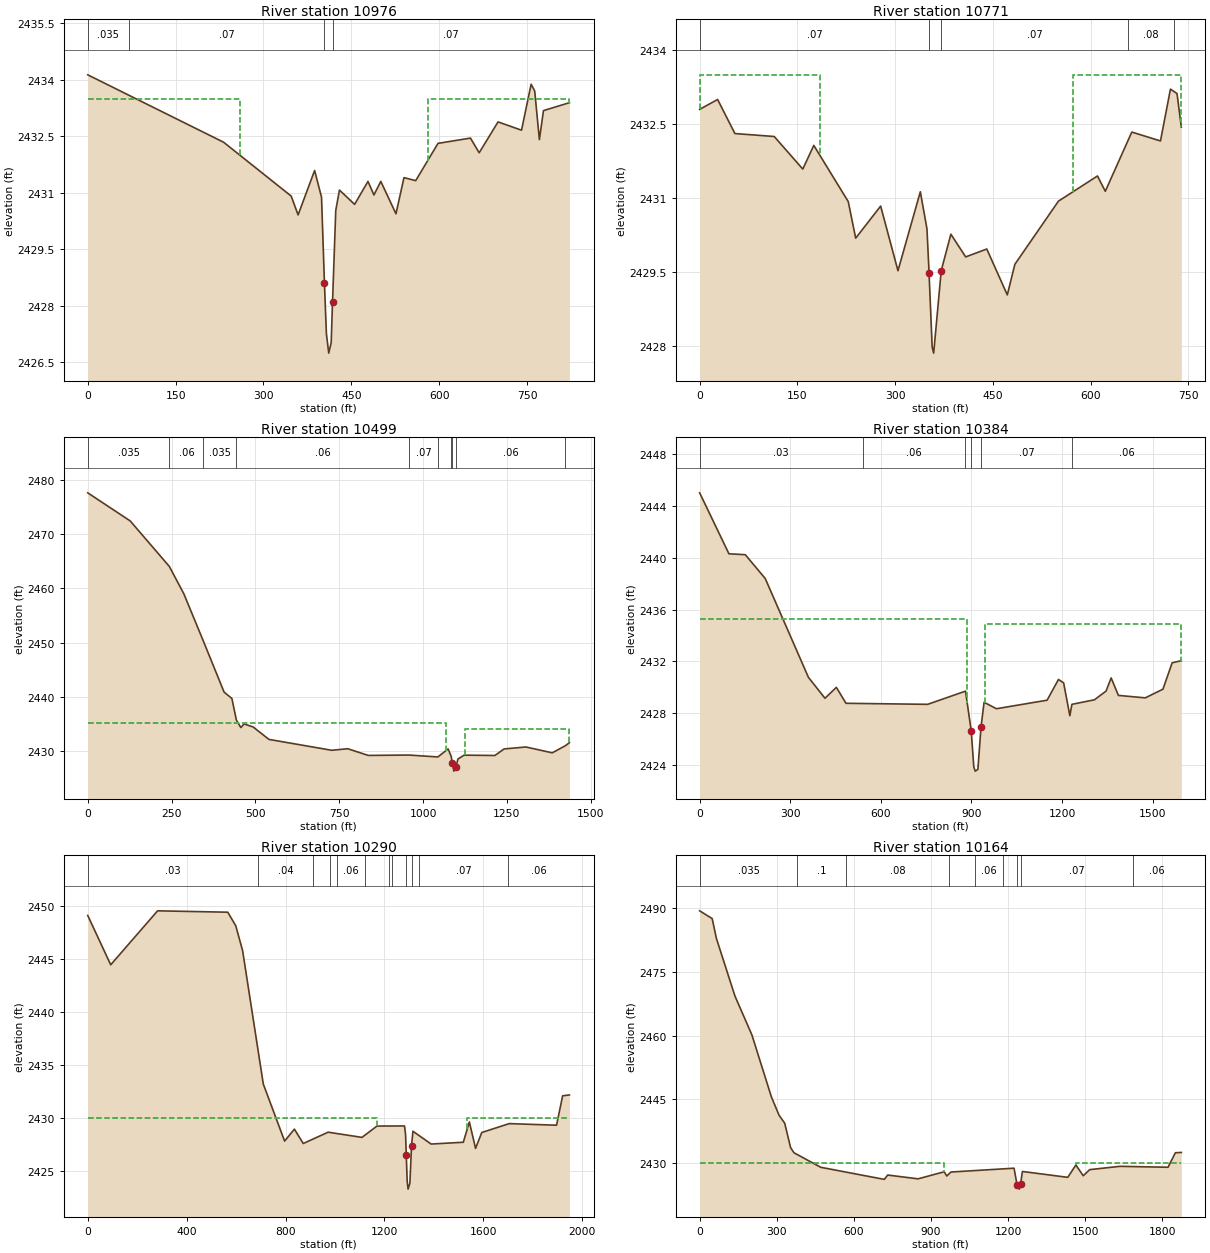
Type RM Length L Ch R = 1 ,10976   ,203,204.8,205.2
XS GIS Cut Line= 2
     2016287.926      308004.698      2015615.71      308478.681
#Sta/Elev= 30
       0 2434.13     232 2432.34   347.4 2430.91   359.2 2430.41   387.4 2431.59
   399.2 2430.88   404.22428.589   407.5 2427.26   411.5 2426.74   415.7 2427.02
     418 2428.11   423.5 2430.53   429.8 2431.07   455.7 2430.69   478.5  2431.3
   488.7 2430.94   500.4  2431.3   526.3 2430.44     540  2431.4     560 2431.32
   598.1 2432.31   653.5 2432.45   668.4 2432.06   700.6 2432.88   740.7 2432.66
   757.1 2433.88   763.2  2433.7   771.2 2432.41   778.2 2433.18   822.5 2433.39
#Mann= 4 ,-1 , 0
       0    .035       0      70     .07       0   404.2    .045       0
     418     .07       0
#XS Ineff= 2 , 0
             260  2433.5   580.5          2433.5
Permanent Ineff=
       F       F
Bank Sta=404.2,418
XS Rating Curve= 0 ,0
Exp/Cntr=0.3,0.1

Type RM Length L Ch R = 1 ,10771   ,268.8,272.7,274.3
XS GIS Cut Line= 4
  2016168.366512  308023.68283262015993.85746277307983.853356324
2015719.54423707308146.5114499582015596.01268152308353.862722488
#Sta/Elev= 30
       0  2432.8    27.6    2433    54.1 2432.31   114.5 2432.25   158.3 2431.59
   175.2 2432.07   228.1 2430.93   239.5 2430.19   277.8 2430.84   304.4 2429.53
   338.7 2431.13   348.9 2430.38   352.1 2429.49   352.1 2429.48   356.9 2427.98
   359.2 2427.86   370.82429.533   385.6 2430.27   408.3 2429.81   440.7 2429.97
   472.2 2429.04   483.8 2429.66   550.7 2430.94   610.6 2431.45   622.6 2431.14
   663.3 2432.34   707.3 2432.16   722.6 2433.21   732.7 2433.12   739.3 2432.44
#Mann= 5 ,-1 , 0
       0     .07       0   352.1    .045       0   370.8     .07       0
  657.91     .08       0  727.91     .07       0
#XS Ineff= 2 , 0
             185  2433.5     573          2433.5
Permanent Ineff=
       F       F
Bank Sta=352.1,370.8
XS Rating Curve= 0 ,0
Exp/Cntr=0.5,0.3

Type RM Length L Ch R = 1 ,10499   ,112.1,114.8,118.5
XS GIS Cut Line= 4
2016755.38471356307781.8973015812016259.50210026307693.346834921
 2015576.6796129307880.2867089812015362.19070477307947.191506013
#Sta/Elev= 30
       0 2477.66   126.6 2472.47   243.3 2464.06   286.6    2459   344.7 2450.28
   406.6 2440.84   429.9 2439.66   443.2 2435.67   456.5 2434.29   466.4 2434.96
   493.2  2434.4   540.4  2432.1   727.7 2430.09   775.3 2430.38   836.5 2429.14
   957.6 2429.21    1044 2428.86  1074.7 2430.34    1084 2428.92  1086.92427.777
  1091.7 2426.24  1098.12427.094    1104 2428.48  1122.3 2429.19  1214.1 2429.13
  1241.6 2430.34  1306.9  2430.7  1385.2 2429.62  1423.8 2430.92  1436.4 2431.49
#Mann= 10 ,-1 , 0
       0    .035       0   243.3     .06       0   344.7    .035       0
   443.2     .06       0   957.6     .07       0    1044     .04       0
    1084     .06       0  1086.9    .045       0  1098.1     .06       0
  1423.8     .07       0
#XS Ineff= 2 , 0
         1068.68  2435.2 1126.04          2434.1
Permanent Ineff=
       F       F
Bank Sta=1086.9,1098.1
XS Rating Curve= 0 ,0
Exp/Cntr(USF)=0,0
Exp/Cntr=0.5,0.3

Type RM Length L Ch R = 1 ,10384   ,96.4,93.7,90.3
XS GIS Cut Line= 4
2016503.93555368307496.6395102432015455.10649519307806.910175458
 2015004.7893588307940.6928513182014973.07066917307941.768061135
#Sta/Elev= 30
       0 2445.03      97 2440.32   151.2 2440.25   217.2 2438.41   360.4 2430.77
   415.1 2429.16   452.8    2430   484.7 2428.77   755.2 2428.69   880.5 2429.71
   899.52426.636   907.9 2423.87   912.6 2423.53   921.5 2423.66   931.92426.944
   942.1 2428.85   982.9 2428.35  1150.8 2429.01  1188.4 2430.61  1205.5 2430.35
  1226.1 2427.81  1232.9 2428.69  1307.5 2429.04  1345.9 2429.71  1362.9 2430.73
  1386.9 2429.38  1475.9 2429.19  1534.4 2429.86  1564.9  2431.9  1595.3 2432.06
#Mann= 6 ,-1 , 0
       0     .03       0     540     .06       0     880     .04       0
   899.5    .045       0   931.9     .07       0 1233.76     .06       0
#XS Ineff= 2 , 0
             886  2435.3     945          2434.9
Permanent Ineff=
       F       F
Bank Sta=899.5,931.9
XS Rating Curve= 0 ,0
Exp/Cntr(USF)=0,0
Exp/Cntr=0.5,0.3

Type RM Length L Ch R = 1 ,10290   ,132.3,126.5,119.3
XS GIS Cut Line= 3
2016760.79333736307152.643969687 2015105.9096828307890.651645723
2014977.09954662307934.520206294
#Sta/Elev= 30
       0  2449.1    92.9 2444.44   282.5 2449.54   566.3 2449.41   598.6 2448.13
   626.4 2445.77     710 2433.17   796.2 2427.78   835.8 2428.91   871.6 2427.55
   972.2 2428.62    1109 2428.13  1169.8  2429.2  1281.1 2429.21  1285.4 2428.41
  1288.22426.482  1291.9    2424  1295.5 2423.24  1302.8 2423.79  1309.5 2427.34
  1315.2 2428.71  1388.9  2427.5  1518.9 2427.67  1543.4 2429.59  1568.5 2427.09
  1593.5 2428.59  1704.4 2429.43    1896 2429.28  1920.7 2432.06  1948.1 2432.14
#Mann= 12 ,-1 , 0
       0     .03       0     690     .04       0     910     .06       0
     980     .07       0    1010     .06       0    1120     .04       0
    1220     .06       0    1230      .1       0  1288.2    .045       0
  1309.5      .1       0    1340     .07       0    1700     .06       0
#XS Ineff= 2 , 0
            1170    2430    1535            2430
Permanent Ineff=
       F       F
Bank Sta=1288.2,1309.5
XS Rating Curve= 0 ,0
Exp/Cntr(USF)=0,0
Exp/Cntr=0.3,0.1

Type RM Length L Ch R = 1 ,10164   ,423.5,418.9,294.3
XS GIS Cut Line= 4
2015661.84557583 306391.294139982015618.06835054307449.907042581
2015339.48600775307760.3273674042014975.69014577307920.768550061
#Sta/Elev= 30
       0 2489.31    48.7 2487.49    65.1 2482.85   137.2  2469.3   203.4 2460.13
     279  2445.6   308.8 2441.28   331.1 2439.37     354 2433.62   367.2 2432.43
   471.4 2429.02   718.5 2426.18   731.7  2427.2   849.9 2426.31   951.7 2427.97
   961.5 2426.97   977.9 2427.91  1223.3 2428.81  1234.9 2424.95  1244.2 2423.89
  1248.8 2425.11  1255.8 2428.04  1432.4 2426.66  1463.9 2429.57  1492.5 2427.04
  1517.6 2428.47  1635.5 2429.25  1822.5 2429.03    1851 2432.44  1874.2 2432.51
#Mann= 9 ,-1 , 0
       0    .035       0     380      .1       0     570     .08       0
     970      .1       0 1069.52     .06       0 1179.52     .07       0
  1234.9    .045       0  1248.8     .07       0 1686.61     .06       0
#XS Ineff= 2 , 0
             950    2430    1465            2430
Permanent Ineff=
       F       F
Bank Sta=1234.9,1248.8
XS Rating Curve= 0 ,0
Exp/Cntr(USF)=0,0
Exp/Cntr=0.5,0.3

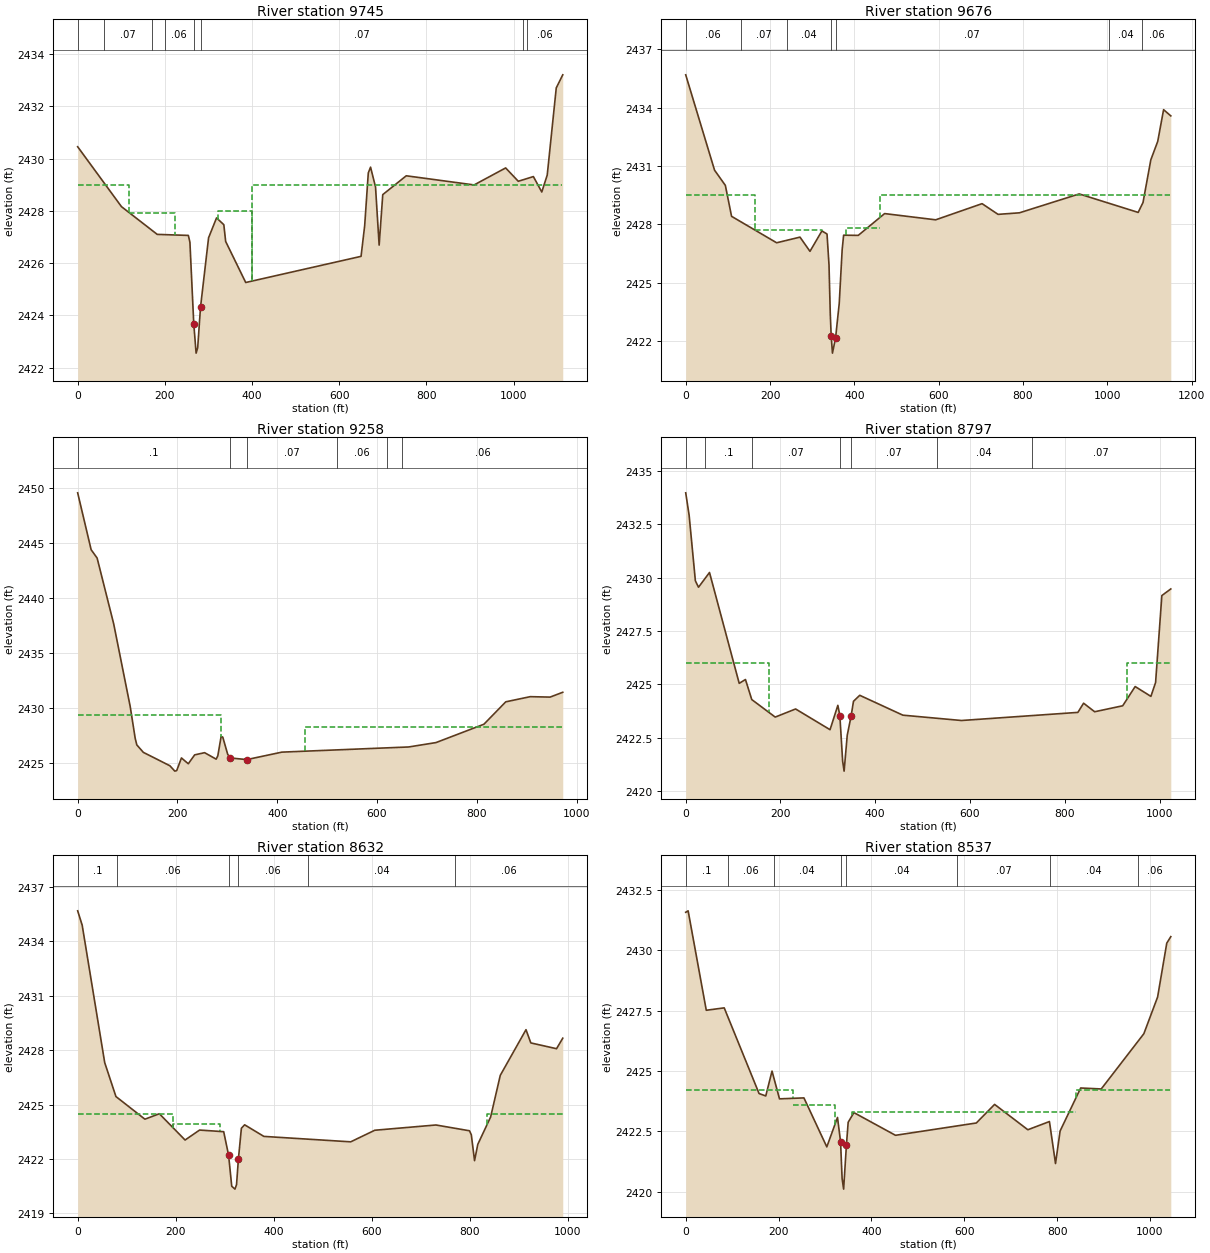
Type RM Length L Ch R = 1 ,9745    ,68.5,68.7,135.1
XS GIS Cut Line= 4
 2015170.2599327307003.6805508012015330.61030555307378.993379995
2015351.52557157307611.3852246972014978.53666082307899.551112128
#Sta/Elev= 30
       0 2430.45   100.5 2428.16   182.5  2427.1   253.9 2427.06   257.5  2426.8
   266.3 2423.69   271.7 2422.56   275.3 2422.76   281.82424.314   300.3 2426.97
   318.6 2427.73   335.3 2427.47   339.5 2426.83   385.5 2425.26   650.1 2426.26
   658.4 2427.43   666.7 2429.45   671.9 2429.67   683.3 2428.91   691.6 2426.69
   699.9 2428.62   753.8 2429.34   909.4 2428.99   981.8 2429.64  1010.8 2429.13
  1045.4 2429.31  1064.7 2428.72  1077.2 2429.37  1097.9  2432.7  1112.8  2433.2
#Mann= 8 ,-1 , 0
       0     .06       0      60     .07       0     170     .04       0
     200     .06       0   266.3    .045       0   281.8     .07       0
 1021.46     .04       0 1031.46     .06       0
#XS Ineff= 4 ,-1
       0     118    2429     118     223 2427.92  322.64     400    2428
     400  1111.6    2429
Permanent Ineff=
       F       F       F       F
Bank Sta=266.3,281.8
XS Rating Curve= 0 ,0
Exp/Cntr(USF)=0,0
Exp/Cntr=0.5,0.3

Type RM Length L Ch R = 1 ,9676    ,412.3,417.7,416.5
XS GIS Cut Line= 5
2015062.30292287306942.9590163992015186.62777806 307193.20263518
2015266.32319806307424.3193531622015277.48055685307602.837093949
2014937.97806768307894.522331126
#Sta/Elev= 30
       0 2435.69    68.4 2430.79      94 2430.01   108.7 2428.42   215.6 2427.06
     271 2427.35   294.7 2426.62     323 2427.67   335.1 2427.51   339.8 2425.93
   342.8 2423.43     3452422.265     348 2421.39   355.42422.173   364.1 2423.95
     371  2426.7   374.5 2427.45   409.2 2427.44   471.7 2428.56   592.8 2428.24
   702.8 2429.07   740.7 2428.52   791.5  2428.6   933.2 2429.57    1073 2428.62
  1084.5 2429.13    1103 2431.32  1119.4 2432.27  1133.3  2433.9  1150.4 2433.58
#Mann= 7 ,-1 , 0
       0     .06       0     130     .07       0     240     .04       0
     345    .045       0   355.4     .07       0 1002.76     .04       0
 1082.76     .06       0
#XS Ineff= 4 ,-1
       0     165  2429.5     165  322.64  2427.7     380     460  2427.8
     460    1148  2429.5
Permanent Ineff=
       F       F       F       F
Bank Sta=345,355.4
XS Rating Curve= 0 ,0
Exp/Cntr(USF)=0,0
Exp/Cntr=0.5,0.3

Type RM Length L Ch R = 1 ,9258    ,460.3,461.1,460
XS GIS Cut Line= 2
2014765.50957939307037.7463457552014900.47447294308000.495919764
#Sta/Elev= 30
       0 2449.57      27 2444.39      39 2443.63    72.2 2437.64   105.3 2430.11
   115.2 2427.24   118.5 2426.62   131.6 2425.94   184.8 2424.72   194.7 2424.23
   198.5 2424.28     208 2425.43   221.7  2424.9   234.5 2425.71   254.4 2425.91
   277.6 2425.32   280.9 2425.63   287.5 2427.38   290.8 2427.33   300.7 2425.76
   306.22425.427     339 2425.28   409.4 2425.96   663.4 2426.43   718.2 2426.83
   814.2  2428.5     858 2430.54     907 2431.01   946.8 2430.97   972.2 2431.41
#Mann= 6 ,-1 , 0
       0      .1       0   306.2    .045       0     339     .07       0
     520     .06       0     620     .04       0     650     .06       0
#XS Ineff= 2 , 0
          287.74 2429.34  454.72         2428.23
Permanent Ineff=
       F       F
Bank Sta=306.2,339
XS Rating Curve= 0 ,0
Exp/Cntr(USF)=0,0
Exp/Cntr=0.3,0.1

Type RM Length L Ch R = 1 ,8797    ,163.7,164.8,166.2
XS GIS Cut Line= 2
2014324.62426045307121.7245017432014444.59305472308138.460033173
#Sta/Elev= 30
       0 2433.97     7.2 2432.92    20.4 2429.85      27 2429.55    50.2 2430.24
   112.9 2425.05   126.1 2425.23   139.4 2424.29   188.9 2423.47   231.9 2423.85
   304.6 2422.88   321.1 2424.02   325.3 2423.54   331.2 2421.41   334.3 2420.94
   340.9 2422.62     349 2423.51   354.1 2424.21   367.3 2424.49   458.3 2423.56
     582 2423.31   827.7 2423.69   839.7 2424.12   863.1 2423.72   922.3    2424
   948.6  2424.9   981.8 2424.44   991.7 2425.09  1004.9 2429.16  1023.8 2429.47
#Mann= 7 ,-1 , 0
       0     .07       0      40      .1       0     140     .07       0
   325.3    .045       0     349     .07       0     530     .04       0
     730     .07       0
#XS Ineff= 2 , 0
             175    2426     932            2426
Permanent Ineff=
       F       F
Bank Sta=325.3,349
XS Rating Curve= 0 ,0
Exp/Cntr(USF)=0,0
Exp/Cntr=0.5,0.3

Type RM Length L Ch R = 1 ,8632    ,95.7,95.3,94.3
XS GIS Cut Line= 2
2014198.65702647307178.7096790212014216.65234561308168.452231741
#Sta/Elev= 30
       0 2435.69     9.2  2434.9    55.2 2427.31    78.1 2425.44   137.2 2424.19
   166.7 2424.49   219.2 2423.04   248.8 2423.59     298  2423.5     3082422.201
   314.4 2420.49     321 2420.33   324.2 2420.58     3282421.987   334.1 2423.69
   340.7 2423.88     380 2423.24   557.2 2422.94   606.3 2423.58   731.1 2423.87
   799.6 2423.55   803.3 2423.33   809.9  2421.9   816.5  2422.8   842.7 2424.31
   862.4 2426.61   914.9 2429.13   924.7  2428.4   977.2 2428.08   989.9 2428.66
#Mann= 6 ,-1 , 0
       0      .1       0      80     .06       0     308    .045       0
     328     .06       0     470     .04       0     770     .06       0
#XS Ineff= 4 ,-1
       0     195  2424.5     195     290  2423.9     356     835 2423.35
     835   989.8  2424.5
Permanent Ineff=
       F       F       F       F
Bank Sta=308,328
XS Rating Curve= 0 ,0
Exp/Cntr(USF)=0,0
Exp/Cntr=0.5,0.3

Type RM Length L Ch R = 1 ,8537    ,158.8,156.9,155.7
XS GIS Cut Line= 3
2014090.68511163307166.7127995942014123.67653005307730.566132659
2014132.67418962308210.441309735
#Sta/Elev= 30
       0 2431.58     5.2 2431.64    44.3 2427.52    82.9 2427.62     158 2424.07
   172.4 2423.97   185.9    2425     202 2423.85   254.6 2423.89   303.9 2421.86
   326.9 2423.08   333.5 2422.08   336.8 2420.56   340.1 2420.11   346.12421.927
   349.9 2422.88   362.3 2423.28   451.8 2422.34   625.9 2422.85   665.3 2423.62
   736.9 2422.57   783.4 2422.91   796.5 2421.17   806.4 2422.52   850.7  2424.3
     895 2424.26   986.8 2426.55  1016.4 2428.07  1036.1  2430.3  1044.8 2430.57
#Mann= 8 ,-1 , 0
       0      .1       0      90     .06       0     190     .04       0
   333.5    .045       0   346.1     .04       0  584.82     .07       0
  784.82     .04       0  974.82     .06       0
#XS Ineff= 4 ,-1
       0     230  2424.2     230     321  2423.6     359     840  2423.3
     840    1044  2424.2
Permanent Ineff=
       F       F       F       F
Bank Sta=333.5,346.1
XS Rating Curve= 0 ,0
Exp/Cntr(USF)=0,0
Exp/Cntr=0.5,0.3

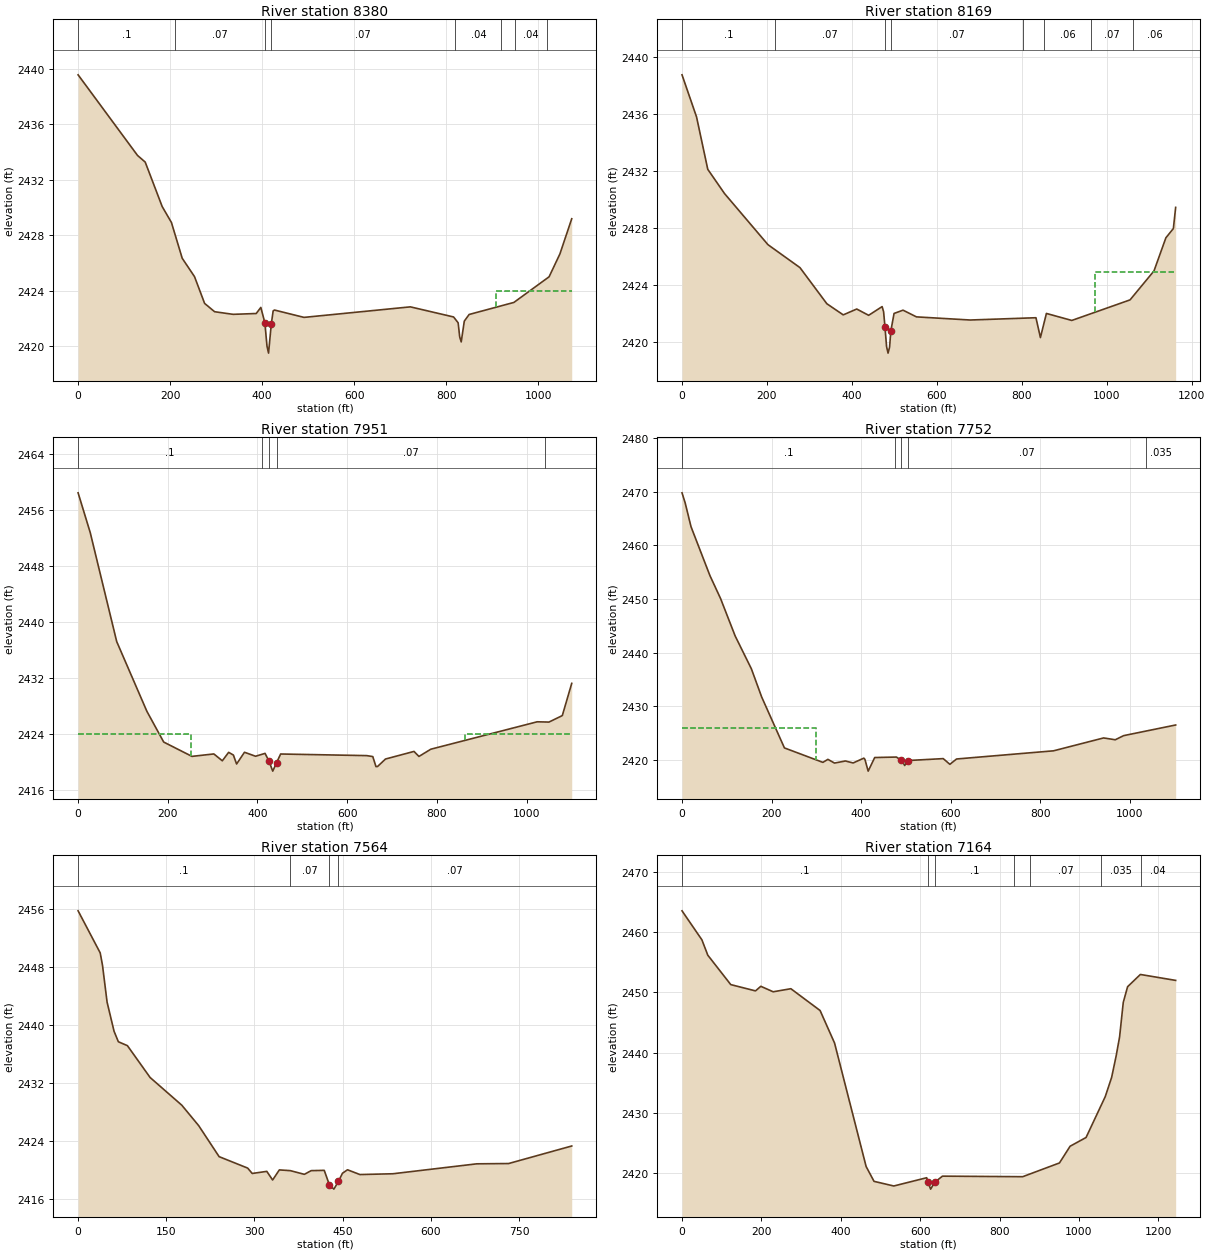
Type RM Length L Ch R = 1 ,8380    ,212.4,210.9,208.5
XS GIS Cut Line= 2
     2013876.219      307146.7862014094.48809839308197.342733021
#Sta/Elev= 30
       0 2439.57   129.2 2433.75   145.9 2433.27   182.8 2430.06   202.9 2428.91
   226.3 2426.33   253.1    2425     275 2423.07   296.7 2422.47   336.9 2422.28
   387.2 2422.34   397.2 2422.78     4062421.671   410.6 2419.98     414 2419.48
   419.92421.573     424 2422.53     427 2422.59   491.1 2422.06   722.3 2422.82
   816.2 2422.09   826.1 2421.67   829.5 2420.65   832.8 2420.29   839.5 2421.79
     850 2422.27   947.3 2423.14  1023.8 2424.99  1047.3 2426.64    1073 2429.18
#Mann= 8 ,-1 , 0
       0      .1       0     210     .07       0     406    .045       0
   419.9     .07       0     820     .04       0     920     .07       0
     950     .04       0    1020     .06       0
#XS Ineff= 2 , 0
                             909            2424
Permanent Ineff=
       F       F
Bank Sta=406,419.9
XS Rating Curve= 0 ,0
Exp/Cntr=0.3,0.1

Type RM Length L Ch R = 1 ,8169    ,217.6,218.7,217.1
XS GIS Cut Line= 3
2013688.65469509307134.1840315892013666.69051693307365.284069799
2014001.39068559308233.056896751
#Sta/Elev= 30
       0 2438.74    34.2 2435.79    60.6 2432.12   100.1 2430.42   202.3 2426.84
   277.7 2425.23     341  2422.7   379.6 2421.92   411.3 2422.33   439.4 2421.89
   471.1  2422.5   474.6 2422.14   477.92421.052   481.6 2419.69   485.1 2419.24
   488.7 2419.66   491.62420.789   499.2 2422.02   520.3 2422.25   551.9 2421.78
   678.5 2421.56   833.3 2421.72   843.8 2420.33   857.9 2422.02   917.7 2421.53
  1054.8 2422.97  1111.2    2425  1139.2 2427.32  1156.8 2427.97  1162.2 2429.45
#Mann= 8 ,-1 , 0
       0      .1       0     220     .07       0   477.9    .045       0
   491.6     .07       0  802.14     .04       0  852.14     .06       0
  962.14     .07       0 1062.14     .06       0
#XS Ineff= 2 , 0
                             972         2424.89
Permanent Ineff=
       F       F
Bank Sta=477.9,491.6
XS Rating Curve= 0 ,0
Exp/Cntr=0.3,0.1

Type RM Length L Ch R = 1 ,7951    ,199.9,198.5,196.8
XS GIS Cut Line= 4
 2013336.4274363307306.0415466412013459.68190207307436.631699191
2013734.36572177308125.3075895242013737.10431293308304.950569795
#Sta/Elev= 30
       0 2458.49    27.1 2452.79    86.1  2437.2   153.4 2427.22   190.9 2422.82
   253.9 2420.77   302.7 2421.12   321.6 2420.14   335.7 2421.35   346.3 2420.96
   353.4 2419.68     371 2421.36   395.7 2420.79   416.9  2421.2   425.62420.097
     434 2418.66   442.62419.861   451.6 2421.11   643.5 2420.88   657.1 2420.74
   664.2 2419.31   667.7 2419.32   685.4 2420.39     749 2421.48     760 2420.76
   786.6  2421.8  1023.7 2425.72  1049.9 2425.68  1079.7 2426.61  1100.7 2431.22
#Mann= 5 ,-1 , 0
       0      .1       0  409.57     .07       0   425.6    .045       0
   442.6     .07       0 1041.01    .035       0
#XS Ineff= 2 , 0
             252    2424     863            2424
Permanent Ineff=
       F       F
Bank Sta=425.6,442.6
XS Rating Curve= 0 ,0
Exp/Cntr=0.3,0.1

Type RM Length L Ch R = 1 ,7752    ,188.5,188.5,186.6
XS GIS Cut Line= 3
2013232.14280943307302.3454849492013244.33726738307517.556259894
2013666.90020822308297.240842992
#Sta/Elev= 30
       0 2469.76       7 2467.89    20.1 2463.45    62.3 2454.35    85.9 2450.11
   118.7  2443.1   154.9 2436.99   177.9 2431.74   228.7 2422.26   314.6 2419.57
   325.8 2420.13   340.6 2419.44   364.9 2419.83   382.1 2419.46   406.1 2420.36
   408.5 2420.12   415.7 2417.94   430.3 2420.47   478.7 2420.56     490 2419.95
   497.4 2418.99   503.6 2419.91   583.3 2420.27   598.2 2419.21   613.1  2420.2
   829.6 2421.72   941.5 2424.12   967.5 2423.78   986.3 2424.55  1102.4 2426.53
#Mann= 5 ,-1 , 0
       0      .1       0  475.56     .07       0     490    .045       0
   503.6     .07       0 1035.56    .035       0
#XS Ineff= 2 , 0
             300  2425.9
Permanent Ineff=
       F       F
Bank Sta=490,503.6
XS Rating Curve= 0 ,0
Exp/Cntr=0.3,0.1

Type RM Length L Ch R = 1 ,7564    ,394,399.1,403.8
XS GIS Cut Line= 2
2012992.49965446307493.904470413     2013434.681      308207.747
#Sta/Elev= 30
       0 2455.77    37.6 2449.97    41.5 2448.27    49.3 2443.18    61.2 2439.15
    68.5 2437.71    83.9 2437.17   122.5 2432.78   176.5 2428.95   205.2 2426.13
   239.9 2421.86   288.5 2420.28   296.2 2419.54     321 2419.83   330.9 2418.64
   342.3 2420.03     361 2419.93   384.9 2419.42   396.5 2419.93   418.7 2419.97
   427.4 2417.99   435.1 2417.38   442.8 2418.44   449.7 2419.57   458.3 2420.05
   479.4 2419.39   535.5  2419.5   678.2 2420.87   732.3 2420.91   839.7 2423.33
#Mann= 4 ,-1 , 0
       0      .1       0     361     .07       0   427.4    .045       0
   442.8     .07       0
Bank Sta=427.4,442.8
XS Rating Curve= 0 ,0
Exp/Cntr=0.3,0.1

Type RM Length L Ch R = 1 ,7164    ,719.6,751.5,740.7
XS GIS Cut Line= 4
2013019.59538074307396.0502333112012806.05371405307628.689122191
 2012906.7481585 308321.397455522012774.80371408  308507.1613444
#Sta/Elev= 30
       0 2463.51    50.1  2458.7    64.9 2456.16   122.8 2451.28   185.1 2450.24
   198.5    2451   229.6 2450.09   274.2  2450.6   347.8 2446.99   384.3 2441.59
   463.8 2421.13   483.7 2418.67   533.5  2417.9   616.4 2419.27   619.7 2418.51
   626.3 2417.38   636.92418.534   656.1 2419.53   858.3 2419.44   950.9 2421.72
   977.7 2424.49  1017.9 2425.94  1066.2 2432.71  1082.3  2435.9  1093.6 2439.43
  1102.4 2442.63  1111.6 2448.33  1122.5 2450.93  1154.7 2452.96  1243.6 2451.98
#Mann= 7 ,-1 , 0
       0      .1       0   619.7    .045       0   636.9      .1       0
  835.79     .04       0  875.79     .07       0 1055.77    .035       0
 1155.77     .04       0
Bank Sta=619.7,636.9
XS Rating Curve= 0 ,0
Exp/Cntr(USF)=0,0
Exp/Cntr=0.3,0.1