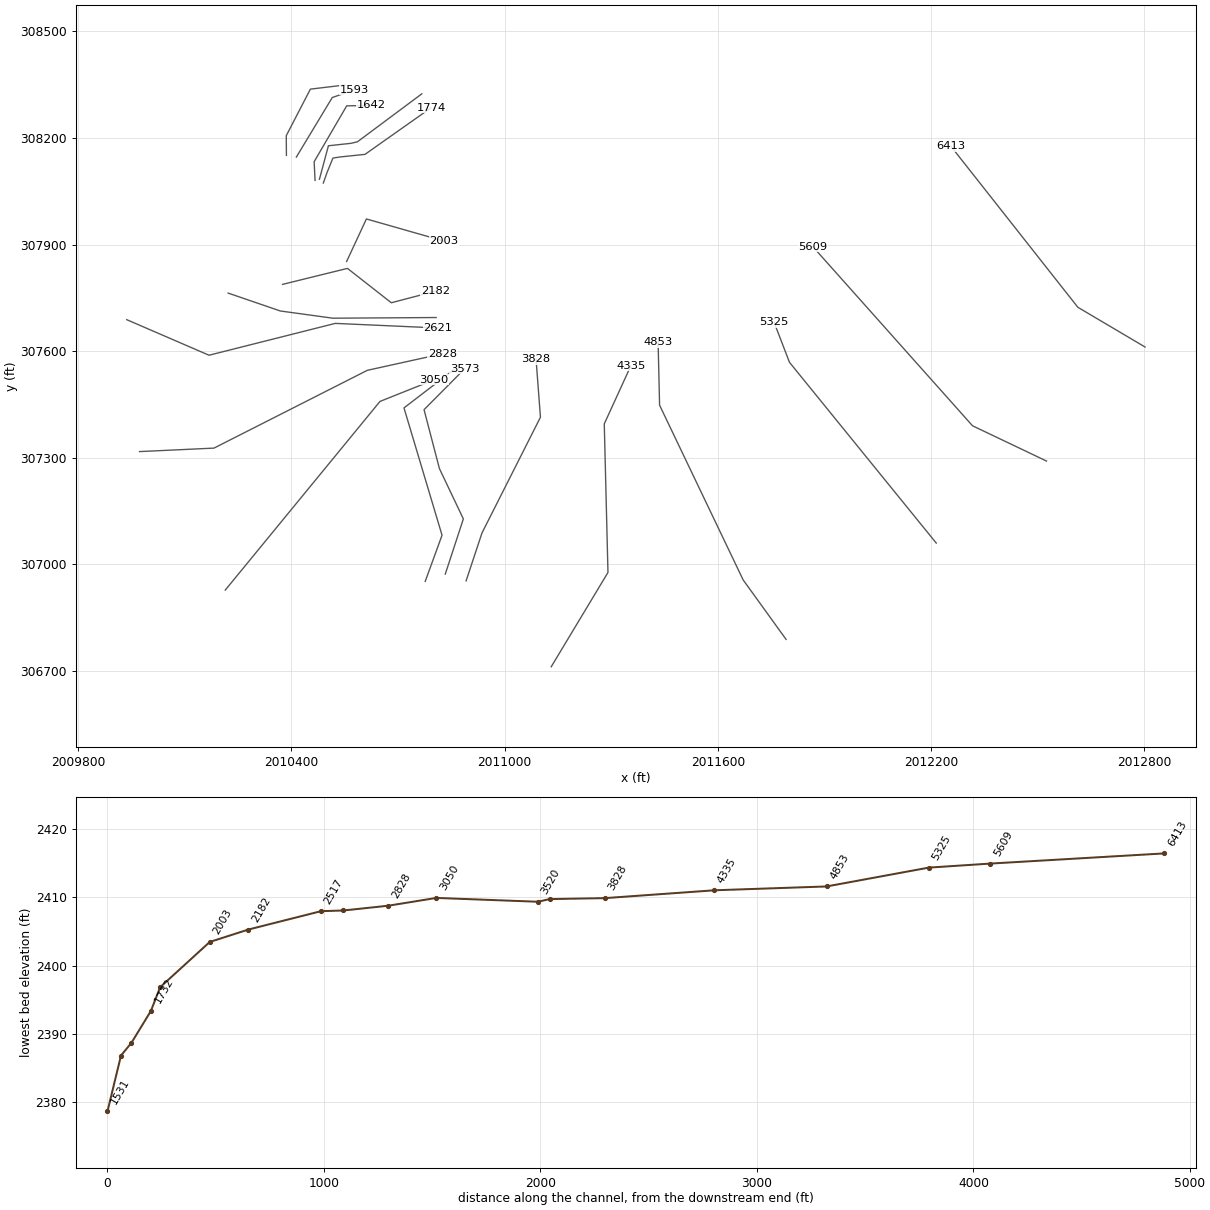
HEC-RAS study COONCK.prj: COONCK

--- COONCK.g01 (geometry) --- (continued)

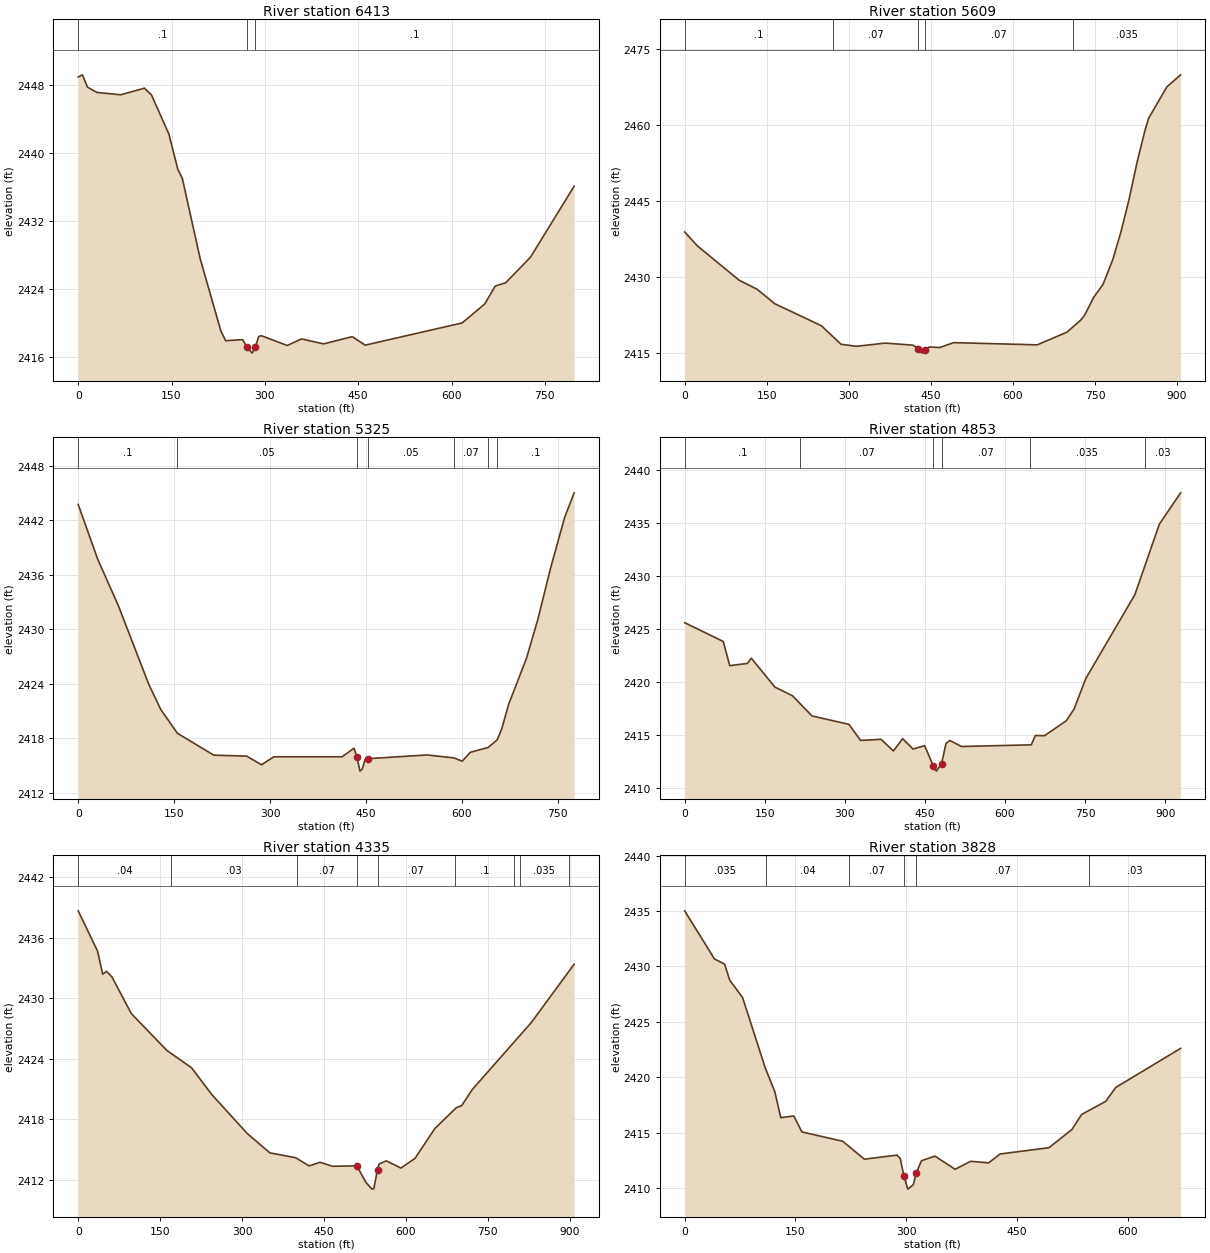
Type RM Length L Ch R = 1 ,6413    ,786.3,803.9,791.3
XS GIS Cut Line= 3
2012801.71118462307611.3469887892012612.49459057307723.320284379
2012255.28381538 308176.76800229
#Sta/Elev= 30
       0 2448.94     6.8 2449.19    14.9 2447.74    30.1 2447.12    68.3 2446.84
   106.4 2447.62   117.8 2446.82   145.7 2442.23   160.1 2438.08   167.4 2436.99
     196 2427.57   229.3 2419.05     237 2417.91   264.4 2418.04   270.7 2417.19
   279.4 2416.45   284.7 2417.15     290  2418.4   294.3  2418.5     336 2417.35
   358.9 2418.12   394.5 2417.54   440.5 2418.39   461.3 2417.39   617.1    2420
   653.5 2422.24   670.2 2424.34   687.2 2424.74   726.9 2427.73   797.1 2436.09
#Mann= 3 ,-1 , 0
       0      .1       0   270.7    .045       0   284.7      .1       0
Bank Sta=270.7,284.7
XS Rating Curve= 0 ,0
Exp/Cntr=0.3,0.1

Type RM Length L Ch R = 1 ,5609    ,283.5,284,286
XS GIS Cut Line= 3
 2012524.3362634307290.3175680772012316.15123453307389.612460786
2011866.65233668307894.269759144
#Sta/Elev= 30
       0 2438.85    23.1 2436.12    99.5 2429.34   132.2 2427.57   164.9 2424.69
   249.9 2420.36   285.7 2416.71     314  2416.3   366.4 2416.94   417.6 2416.53
   426.9 2415.81   433.8 2414.96   439.12415.543   447.2 2416.17   466.4 2416.07
   491.6 2417.03   644.5 2416.59   698.8  2419.1   724.3 2421.51   731.3 2422.49
   747.5 2425.95   764.6  2428.5   782.7 2433.45   797.5  2438.9   812.3 2445.29
     827 2452.65   841.8 2459.07   848.1 2461.28   881.3 2467.46   906.5 2469.84
#Mann= 5 ,-1 , 0
       0      .1       0  270.65     .07       0   426.9    .045       0
   439.1     .07       0  710.65    .035       0
Bank Sta=426.9,439.1
XS Rating Curve= 0 ,0
Exp/Cntr=0.3,0.1

Type RM Length L Ch R = 1 ,5325    ,473.5,472.5,465.4
XS GIS Cut Line= 3
2012214.05869256307059.3838410352011801.15364551307568.311068554
2011757.96285251307680.707136349
#Sta/Elev= 30
       0 2443.72    30.4 2437.71    62.9 2432.56   110.6 2423.89   129.1 2421.16
   155.1 2418.54     212 2416.13   263.5 2416.02   286.8 2415.07   306.1 2415.95
   412.8 2415.95   431.4 2416.89   435.9 2415.95   440.8 2414.37   444.4 2414.61
   448.6 2415.63   452.8 2415.74   545.7 2416.15   587.3 2415.83   600.7 2415.47
   613.4 2416.44   641.4 2416.98   655.4 2417.81   662.6 2419.04   673.2  2421.7
   701.1 2426.76   718.9 2431.04   739.1 2436.76     761 2442.31   775.8    2445
#Mann= 7 ,-1 , 0
       0      .1       0   155.1     .05       0   435.9    .045       0
   452.8     .05       0   587.3     .07       0   641.4    .035       0
   655.4      .1       0
Bank Sta=435.9,452.8
XS Rating Curve= 0 ,0
Exp/Cntr=0.3,0.1

Type RM Length L Ch R = 1 ,4853    ,452.7,517.6,492.2
XS GIS Cut Line= 4
2011791.57936371306788.0993600722011670.83181806306955.524136072
2011435.68263073307447.5510499852011431.48795162307624.749330034
#Sta/Elev= 30
       0  2425.6    72.3 2423.83    84.4 2421.55   117.2 2421.76   124.9 2422.25
     169 2419.53     202 2418.71   238.5 2416.81   307.7 2416.02   329.6  2414.5
   367.8 2414.61   391.1 2413.51   408.3 2414.67   427.7 2413.69   449.5 2414.01
     4662412.074   471.3 2411.61   481.1 2412.28   489.5 2414.22   496.7  2414.5
   518.6 2413.93   649.4 2414.09   656.8 2414.97     674 2414.95   714.9 2416.36
   729.5 2417.47   751.3 2420.33   843.2 2428.23   889.2 2434.89     929 2437.84
#Mann= 6 ,-1 , 0
       0      .1       0  216.42     .07       0     466    .045       0
   481.1     .07       0  646.42    .035       0  861.76     .03       0
#XS Ineff= 2 , 0
          105.92 2418.39
Permanent Ineff=
       F       F
Bank Sta=466,481.1
XS Rating Curve= 0 ,0
Exp/Cntr=0.3,0.1

Type RM Length L Ch R = 1 ,4335    ,478.1,506.7,471.8
XS GIS Cut Line= 4
2011130.72790599306710.9475080222011290.45012823306976.572508022
2011280.03346154307394.975285783 2011354.6862393307558.169730246
#Sta/Elev= 30
       0 2438.68    35.4 2434.68    44.9 2432.39    52.1 2432.67    61.7 2432.12
    97.2 2428.48   162.3 2424.82   207.5  2423.1   244.5 2420.44   309.9 2416.55
   350.9 2414.65     398 2414.17   422.9 2413.35   442.6 2413.72   465.3 2413.32
   510.22413.361   526.7 2411.72   537.8 2411.05   541.1 2411.09   547.92412.986
   550.9 2413.55     564 2413.86   590.8 2413.14   616.6 2414.11   652.7 2417.05
     692 2419.13   701.9 2419.33   721.6 2420.95   829.5 2427.59   907.9 2433.38
#Mann= 9 ,-1 , 0
       0     .04       0     170     .03       0  399.95     .07       0
   510.2    .045       0   547.9     .07       0  689.95      .1       0
  798.48     .03       0  808.48    .035       0  898.48     .03       0
Bank Sta=510.2,547.9
XS Rating Curve= 0 ,0
Exp/Cntr(USF)=0,0
Exp/Cntr=0.3,0.1

Type RM Length L Ch R = 1 ,3828    ,230.4,254.8,258.4
XS GIS Cut Line= 4
2010891.27394248306952.8829022962010936.07831115307088.102568943
2011100.46438793307413.6697347522011088.09825779307577.480823278
#Sta/Elev= 30
       0 2435.01    40.3 2430.67    54.1  2430.2      61 2428.75    78.3  2427.2
   109.1 2420.83   122.1 2418.68   130.1 2416.35   147.7  2416.5   158.7 2415.06
   213.9 2414.22   243.3  2412.6   287.4 2412.97   291.8 2412.67   296.7 2411.11
   302.1  2409.9   309.4 2410.29   313.8  2411.4   320.5 2412.46   338.8 2412.88
   366.2 2411.69   387.1 2412.41   411.5 2412.27     427 2413.07   493.2 2413.64
   524.3 2415.28   537.4 2416.64   570.1 2417.82   583.5 2419.07   671.4  2422.6
#Mann= 6 ,-1 , 0
       0    .035       0     110     .04       0  222.45     .07       0
   296.7    .045       0   313.8     .07       0  547.16     .03       0
Bank Sta=296.7,313.8
XS Rating Curve= 0 ,0
Exp/Cntr=0.5,0.3

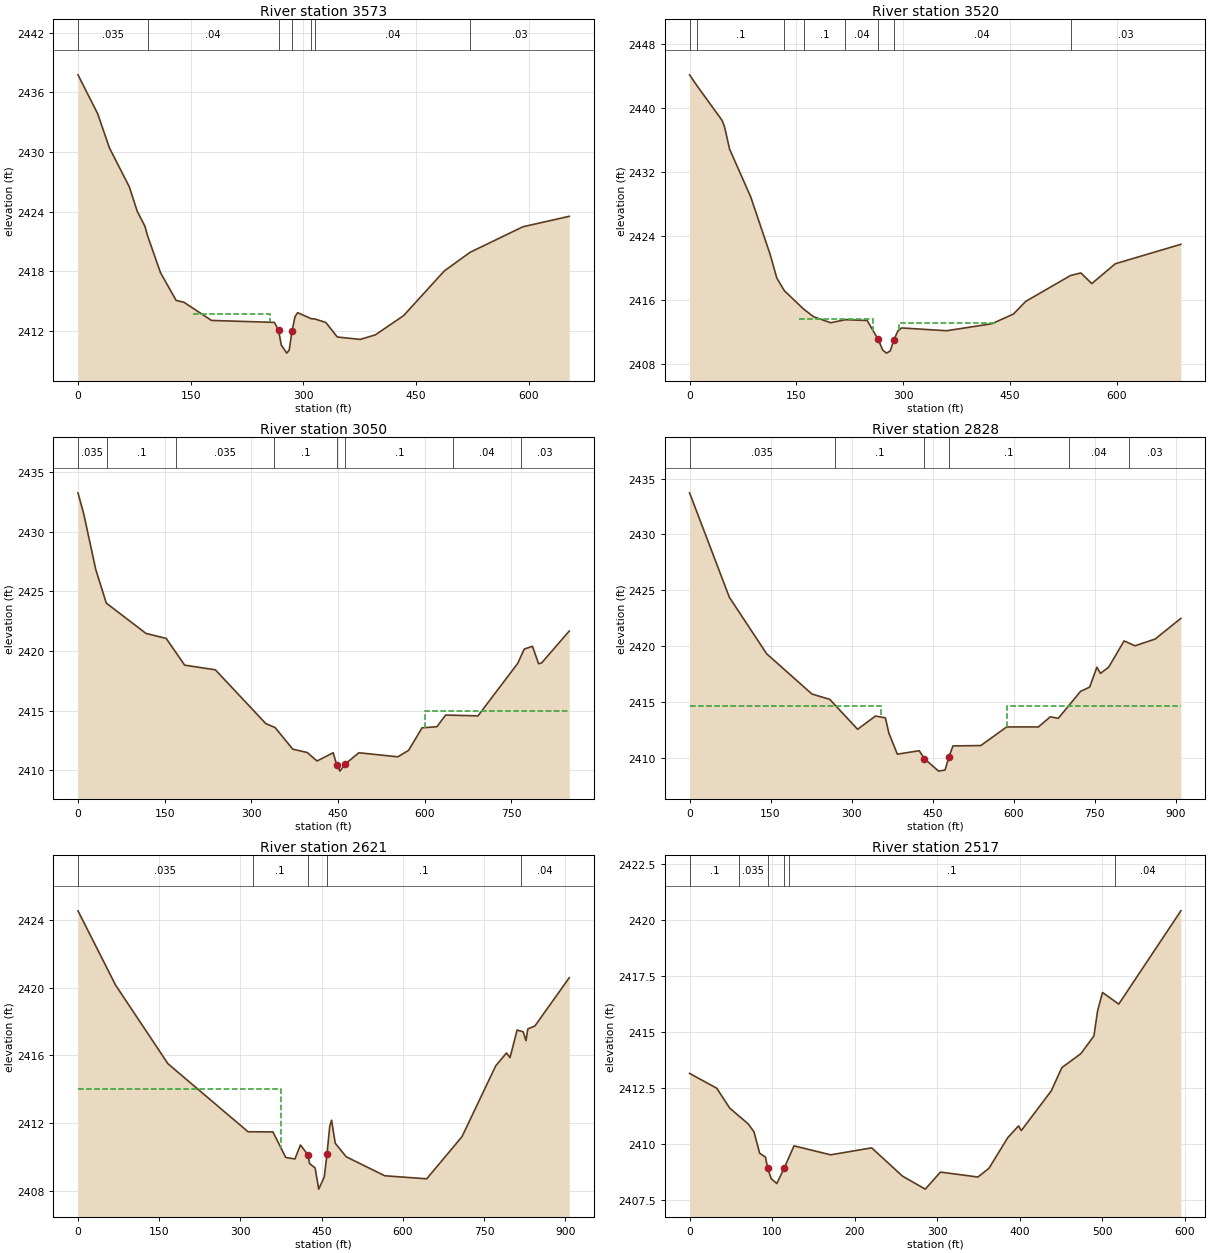
Type RM Length L Ch R = 1 ,3573    ,55.8,53.5,51.7
XS GIS Cut Line= 5
2010832.69136532306972.0037128782010883.56452032307127.345090632
 2010816.2275637 307269.06795454 2010772.9524262307434.935893596
2010886.91945406307549.844882295
#Sta/Elev= 30
       0 2437.75    26.2 2433.84    41.8 2430.41    68.4 2426.47    78.8 2424.03
    89.1 2422.52    92.6 2421.56   109.8 2417.85   130.6 2415.06   140.9 2414.88
   177.6 2413.05   261.3 2412.85   266.9 2412.05   270.5 2410.57   277.8 2409.76
     281 2410.07   284.8 2411.98   288.7 2413.43   292.3 2413.83   310.3 2413.22
   315.4 2413.19   329.8 2412.84     345 2411.38   375.5 2411.14   395.7  2411.6
   433.2 2413.53   487.4 2418.03   521.9 2419.91     592 2422.47   653.6 2423.52
#Mann= 7 ,-1 , 0
       0    .035       0    92.6     .04       0   266.9    .045       0
   284.8     .04       0   310.3      .1       0   315.4     .04       0
   521.9     .03       0
#XS Ineff= 2 ,-1
     153     255  2413.7     300     441  2413.2
Permanent Ineff=
       F       F
Bank Sta=266.9,284.8
XS Rating Curve= 0 ,0
Exp/Cntr=0.5,0.3

Type RM Length L Ch R = 1 ,3520    ,466.2,469.9,416.9
XS GIS Cut Line= 4
 2010776.2353707306951.4168833122010823.55190249307081.423158785
 2010716.5224196307439.9631129422010857.29755477307547.961261603
#Sta/Elev= 30
       0 2444.18    10.8 2442.77    45.7 2438.48    49.2 2437.65    56.2 2434.89
    85.8 2428.93   113.3 2421.68   122.5 2418.77     133 2417.19   160.3 2414.87
   174.2 2413.92   198.2 2413.17   218.7 2413.55   249.5 2413.45   264.82411.095
   271.3 2409.75   276.6 2409.37   281.9 2409.65   286.82410.987   292.4 2412.12
   297.7 2412.52     361 2412.17   424.7 2413.05   454.9 2414.26   472.1 2415.84
   535.1 2419.08   549.6  2419.4   564.9 2418.07     598 2420.55     690 2422.98
#Mann= 8 ,-1 , 0
       0    .035       0    10.8      .1       0     133     .04       0
   160.3      .1       0   218.7     .04       0   264.8    .045       0
   286.8     .04       0   535.1     .03       0
#XS Ineff= 2 ,-1
     153     258  2413.6     294     429  2413.2
Permanent Ineff=
       F       F
Bank Sta=264.8,286.8
XS Rating Curve= 0 ,0
Exp/Cntr=0.5,0.3

Type RM Length L Ch R = 1 ,3050    ,212.4,221.8,206.5
XS GIS Cut Line= 3
2010213.63157981306926.9433284262010649.00689568307458.216752647
2010800.89077156307518.934521803
#Sta/Elev= 30
       0 2433.25    10.1 2431.46    30.8 2426.82      49 2424.01   117.7 2421.47
   152.7 2421.05   184.7 2418.81   237.8 2418.42   325.2 2413.91   341.3 2413.58
   371.8 2411.77   396.8 2411.49   413.8 2410.78   441.8 2411.47   447.7 2410.47
   453.4 2409.93   462.7 2410.53   486.3 2411.47   553.7 2411.13   572.3 2411.67
   595.6 2413.56   621.3 2413.65   636.4 2414.63   692.4 2414.56   761.2 2418.96
   772.5 2420.16   786.7 2420.39   797.3 2418.93   802.6    2419   850.4 2421.67
#Mann= 8 ,-1 , 0
       0    .035       0      50      .1       0     170    .035       0
     340      .1       0   447.7    .045       0   462.7      .1       0
     650     .04       0  766.88     .03       0
#XS Ineff= 2 , 0
                             601            2415
Permanent Ineff=
       F       F
Bank Sta=447.7,462.7
XS Rating Curve= 0 ,0
Exp/Cntr=0.3,0.1

Type RM Length L Ch R = 1 ,2828    ,211.1,207.7,200.9
XS GIS Cut Line= 4
2009972.50976992307316.9517581112010181.89924071307326.740779618
2010613.38257108307545.7790067492010824.56089676307592.356194696
#Sta/Elev= 30
       0 2433.73    73.7 2424.37   142.7 2419.31   226.6  2415.7   259.7 2415.22
   311.2 2412.54   344.3 2413.73   362.7 2413.56     369 2412.21   384.8 2410.31
   425.3 2410.62   434.9  2409.9   461.1 2408.79   473.1 2408.89   480.5 2410.09
   487.8 2411.05   539.3 2411.08   587.2 2412.75     646 2412.75   668.1 2413.66
   682.8 2413.52   724.1 2415.94   740.9 2416.32   754.3  2418.1     761 2417.55
   776.2 2418.11   804.7 2420.46   824.9 2420.02   862.3 2420.63   909.8 2422.48
#Mann= 6 ,-1 , 0
       0    .035       0  269.62      .1       0   434.9    .045       0
   480.5      .1       0  703.51     .04       0  813.51     .03       0
#XS Ineff= 2 , 0
          354.37 2414.61  587.04         2414.65
Permanent Ineff=
       F       F
Bank Sta=434.9,480.5
XS Rating Curve= 0 ,0
Exp/Cntr=0.3,0.1

Type RM Length L Ch R = 1 ,2621    ,107.2,103.2,88
XS GIS Cut Line= 4
2009936.35746903307688.421017694 2010167.9804236307588.268027396
2010523.16323598307677.9233126832010811.60660473307665.031828913
#Sta/Elev= 30
       0 2424.53    69.5 2420.14   166.1  2415.5   314.1 2411.48   360.1 2411.47
   383.8 2409.96   400.7 2409.87   410.9  2410.7   424.4 2410.13   427.8  2409.6
     438 2409.34   444.7 2408.09   454.9 2408.81   459.9 2410.15     465  2411.8
   468.4 2412.16   475.2  2410.8   495.5    2410   566.6 2408.88   644.1  2408.7
   709.3 2411.19   771.7 2415.38   791.4 2416.13     798 2415.86   811.1 2417.49
   822.4 2417.38   827.5 2416.86   830.8 2417.55     844 2417.73   907.4 2420.58
#Mann= 5 ,-1 , 0
       0    .035       0  322.35      .1       0   424.4    .045       0
   459.9      .1       0  818.67     .04       0
#XS Ineff= 2 , 0
             375    2414
Permanent Ineff=
       F       F
Bank Sta=424.4,459.9
XS Rating Curve= 0 ,0
Exp/Cntr=0.3,0.1

Type RM Length L Ch R = 1 ,2517    ,335.6,335.5,315.5
XS GIS Cut Line= 4
2010221.70815122307763.2668556522010368.66449703307712.845280199
2010516.63590451 307692.521696632010806.95540006307694.439249262
#Sta/Elev= 30
       0 2413.15    32.9 2412.49    48.7  2411.6      71  2410.9      78 2410.55
    84.9 2409.59    91.9 2409.42    94.6 2408.93    98.8 2408.46   105.7 2408.24
   114.8 2408.94   126.5 2409.92   170.9 2409.52   220.6 2409.83   257.9 2408.57
   285.5 2407.99   303.9 2408.75   349.3 2408.53   362.7 2408.92   385.5 2410.29
   398.5 2410.81   401.8  2410.6   438.1 2412.37     451 2413.41     474 2414.03
   489.8 2414.82   494.2 2415.93   500.2 2416.76   519.9 2416.24   595.1  2420.4
#Mann= 6 ,-1 , 0
       0      .1       0      60    .035       0    94.6    .045       0
   114.8    .035       0     120      .1       0  514.73     .04       0
Bank Sta=94.6,114.8
XS Rating Curve= 0 ,0
Exp/Cntr(USF)=0,0
Exp/Cntr=0.3,0.1

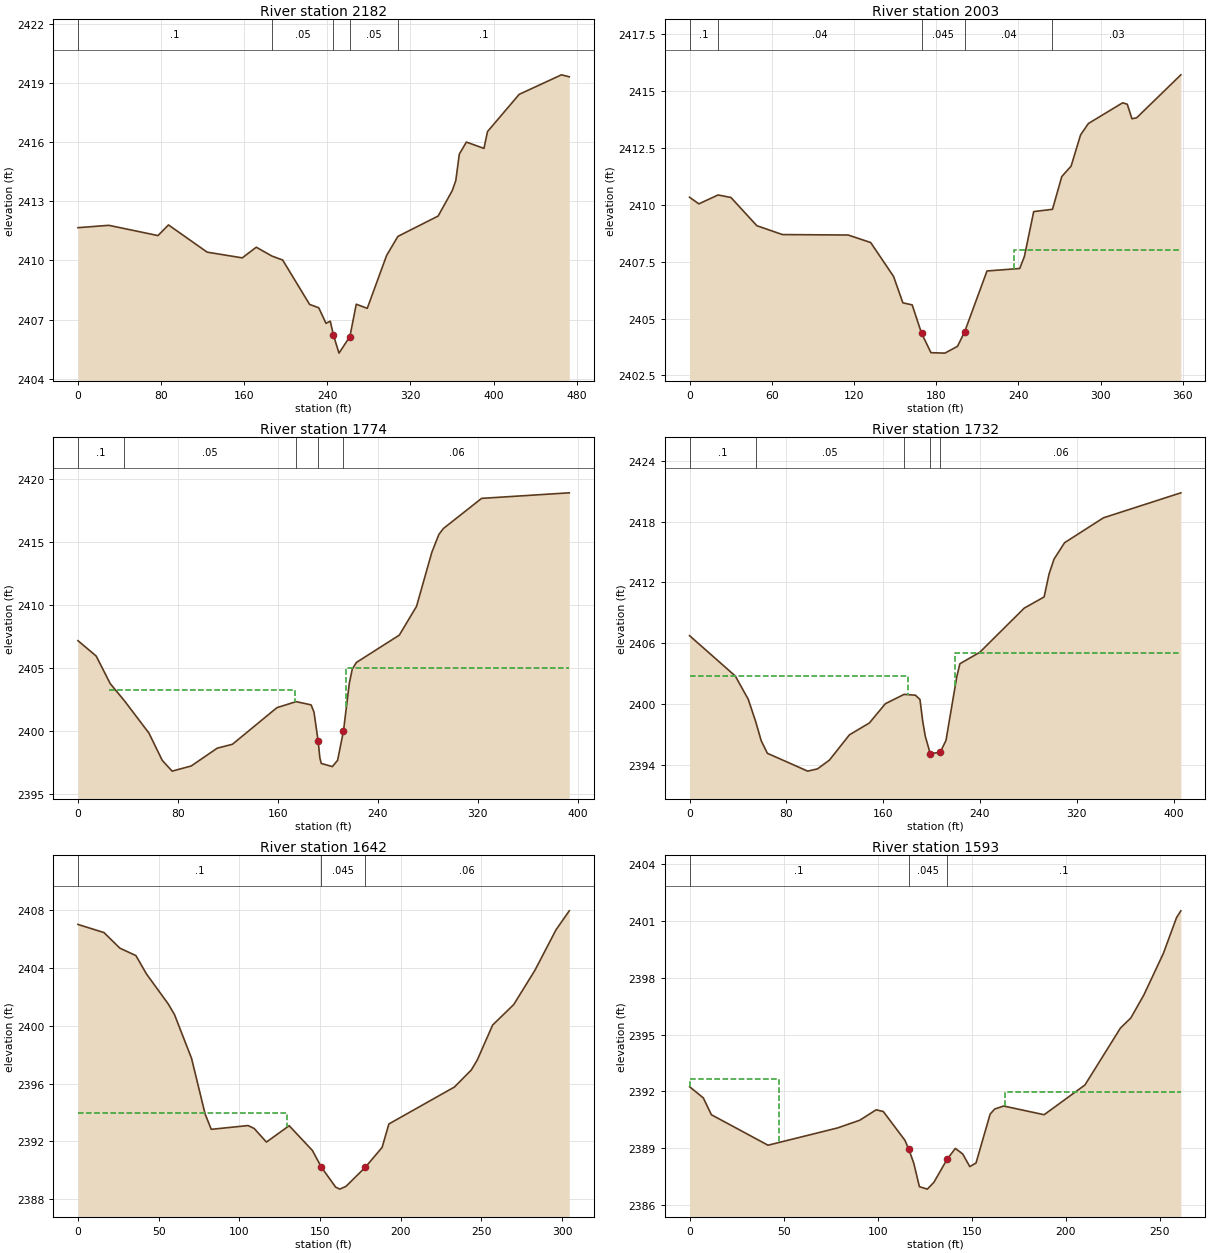
Type RM Length L Ch R = 1 ,2182    ,173.3,178.5,182.6
XS GIS Cut Line= 4
2010374.90831201307787.7948956182010557.44648117307832.803370076
2010680.87344247307736.0209351042010804.66818907307768.431282063
#Sta/Elev= 30
       0 2411.66    29.7 2411.78      77 2411.26    87.1  2411.8   124.3 2410.42
   158.1 2410.13   171.6 2410.67   186.7 2410.22     197 2410.02   222.9 2407.77
   231.7  2407.6   238.7 2406.81   242.8 2406.92   245.9 2406.21   251.2  2405.3
   261.7 2406.14   267.8 2407.78   278.4 2407.57     297 2410.25   307.9 2411.22
   346.6 2412.25   360.2 2413.54   363.6 2414.05     367 2415.39   373.8    2416
   390.7 2415.68   394.1 2416.53   424.6 2418.42   465.3 2419.41   472.8 2419.31
#Mann= 5 ,-1 , 0
       0      .1       0   186.7     .05       0   245.9    .045       0
   261.7     .05       0   307.9      .1       0
Bank Sta=245.9,261.7
XS Rating Curve= 0 ,0
Exp/Cntr=0.3,0.1

Type RM Length L Ch R = 1 ,2003    ,215,229.3,243.5
XS GIS Cut Line= 3
2010555.04861006307852.1081424722010610.78781443307971.995176803
2010828.52557961307909.829962568
#Sta/Elev= 30
       0 2410.33     6.8 2410.04    20.8 2410.43    30.2 2410.32    49.1 2409.08
    67.8 2408.69   115.8 2408.67   132.2 2408.34   148.9 2406.85   155.7 2405.69
   162.5  2405.6   169.3 2404.36   176.2  2403.5   186.4 2403.48   195.6 2403.78
   200.8 2404.42   217.1 2407.09     241  2407.2   244.4 2407.73   251.2  2409.7
   264.9  2409.8   271.7 2411.24   278.5  2411.7   285.4 2413.07   291.1 2413.57
   316.1 2414.48   319.5 2414.42   322.9 2413.78   326.3 2413.82   358.6 2415.71
#Mann= 5 ,-1 , 0
       0      .1       0    20.8     .04       0   169.3    .045       0
   200.8     .04       0   264.9     .03       0
#XS Ineff= 2 , 0
                             237            2408
Permanent Ineff=
       F       F
Bank Sta=169.3,200.8
XS Rating Curve= 0 ,0
Exp/Cntr=0.5,0.3

Type RM Length L Ch R = 1 ,1774    ,43.1,42.4,43.1
XS GIS Cut Line= 6
2010489.51042184 308073.115029752010500.06156846308102.850647377
2010516.58466137308143.4502470882010538.30072633308146.754865669
 2010606.7535398  308153.83619122010792.37641173308284.871728459
#Sta/Elev= 30
       0 2407.19    14.6 2405.97    25.8 2403.79    37.1 2402.44    56.8 2399.87
    67.5  2397.7    75.4 2396.85    90.7 2397.26   111.5 2398.67   123.7 2398.98
   159.3 2401.88   174.7 2402.36   186.7  2402.1     189 2401.52   192.3 2399.25
   193.7  2397.9   194.8 2397.46   203.7 2397.21   207.9 2397.71   212.6 2400.03
   217.3 2403.83   219.6 2404.92   222.9 2405.46   257.3 2407.63   271.1 2409.91
   283.3 2414.18     289 2415.61   292.6 2416.08   323.2 2418.47   393.4 2418.91
#Mann= 5 ,-1 , 0
       0      .1       0    37.1     .05       0   174.7     .06       0
   192.3    .045       0   212.6     .06       0
#XS Ineff= 3 ,-1
   24.84  173.912403.286     180     185  2397.2     215   393.4    2405
Permanent Ineff=
       F       F       F
Bank Sta=192.3,212.6
XS Rating Curve= 0 ,0
Exp/Cntr=0.5,0.3

Type RM Length L Ch R = 1 ,1732    ,85,90.1,94.3
XS GIS Cut Line= 5
2010478.61267891308083.8230240162010503.87459853308178.060392903
2010567.57020519308184.994023536 2010585.5095632308189.242818855
 2010766.6062349308324.258931956
#Sta/Elev= 30
       0 2406.75    37.8 2402.77    48.5 2400.47    54.6 2398.29    59.2 2396.39
    64.3 2395.15    97.6 2393.39   105.7 2393.61   115.6 2394.48   132.1 2396.97
   148.6 2398.14   161.8 2400.04   177.3 2400.96   186.6 2400.88   190.4 2400.46
   192.7  2398.3   194.8 2396.83   198.9 2395.12   207.1 2395.24   211.9 2396.42
   220.9 2402.74   223.4 2403.98   239.8 2405.11   276.6 2409.47     293 2410.57
   297.1 2412.84   301.2  2414.3   309.9 2415.92   342.1 2418.38     406 2420.84
#Mann= 5 ,-1 , 0
       0      .1       0    54.6     .05       0   177.3     .05       0
   198.9    .045       0   207.1     .06       0
#XS Ineff= 2 , 0
          180.57 2402.77  219.53            2405
Permanent Ineff=
       F       F
Bank Sta=198.9,207.1
XS Rating Curve= 0 ,0
Exp/Cntr=0.5,0.3

Type RM Length L Ch R = 1 ,1642    ,48.6,48.3,47.9
XS GIS Cut Line= 4
2010466.31818378308080.6089663362010463.71401712308133.213133022
2010555.38068375308290.5047996792010625.17235044308291.546466351
#Sta/Elev= 30
       0 2406.99    16.1 2406.43      26 2405.35    35.9 2404.84    42.4 2403.58
      56 2401.49    59.8 2400.77    70.4 2397.74    78.8  2393.9    82.6 2392.84
   105.4  2393.1   109.2  2392.9   116.8 2391.96   130.9 2393.09   145.3 2391.38
   150.9 2390.22   159.7 2388.85   162.3 2388.71   166.1  2388.9     178 2390.21
   188.5 2391.59   192.7 2393.21   233.3 2395.76   243.8 2396.94   247.5 2397.63
     257 2400.04   270.1 2401.46   283.2 2403.82   296.3 2406.62   304.5 2407.93
#Mann= 3 ,-1 , 0
       0      .1       0   150.9    .045       0     178     .06       0
#XS Ineff= 2 , 0
          129.81 2393.99
Permanent Ineff=
       F       F
Bank Sta=150.9,178
XS Rating Curve= 0 ,0
Exp/Cntr(USF)=0,0
Exp/Cntr=0.3,0.1

Type RM Length L Ch R = 1 ,1593    ,61.3,62.3,63.1
XS GIS Cut Line= 3
2010413.66939698  308146.28277732010514.69630789308313.874148201
 2010576.5398842308335.590213163
#Sta/Elev= 30
       0 2392.25     7.3 2391.66    11.6 2390.77    41.7 2389.16    78.6 2390.07
    90.5 2390.48    99.2 2391.03     103 2390.94   114.5 2389.42   116.62388.936
   119.2 2388.21   122.2 2386.97   126.4 2386.84   129.9  2387.2   136.92388.414
   141.3 2388.99   145.2  2388.7     149 2388.03   152.3 2388.22   159.8  2390.8
   162.2 2391.07     167 2391.23   188.5 2390.77   210.2 2392.34   229.1 2395.35
   234.6 2395.88   241.5 2397.09   251.9 2399.29   258.9 2401.18   261.2 2401.54
#Mann= 3 , 0 , 0
       0      .1       0   116.6    .045       0   136.9      .1       0
#XS Ineff= 2 , 0
           47.65 2392.68  167.44         2391.95
Permanent Ineff=
       F       F
Bank Sta=116.6,136.9
XS Rating Curve= 0 ,0
Exp/Cntr(USF)=0,0
Exp/Cntr=0.3,0.1

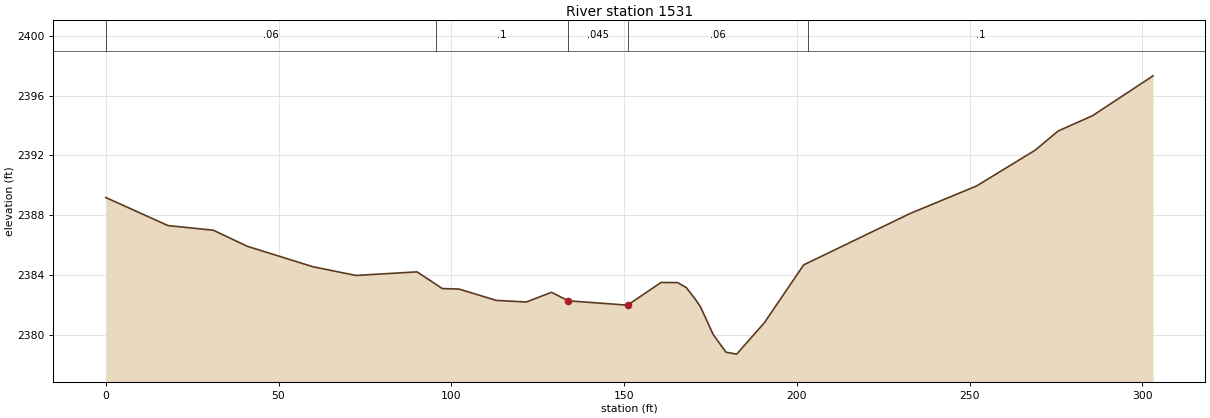
Type RM Length L Ch R = 1 ,1531    ,66.2,63.3,58.7
XS GIS Cut Line= 4
2010385.71583701308150.9121037632010385.29164097  308206.4817852
2010453.16300761308337.5583620262010552.42488132308349.435851189
#Sta/Elev= 30
       0 2389.18      18  2387.3    31.1 2386.99      41 2385.91      60 2384.54
    72.4 2383.96    90.1  2384.2    97.4 2383.08   102.2 2383.05     113 2382.29
   121.7 2382.18     129 2382.83   133.9 2382.26     151 2381.97   160.7 2383.49
   165.5 2383.48     168 2383.15   170.4 2382.44   172.1 2381.87   175.8    2380
   179.5 2378.82   182.6 2378.69   190.6 2380.79     202 2384.67   232.7  2388.1
     252 2389.95     269 2392.35   275.6 2393.63   285.6 2394.66   303.1 2397.33
#Mann= 5 ,-1 , 0
       0     .06       0   95.57      .1       0   133.9    .045       0
     151     .06       0  203.18      .1       0
Bank Sta=133.9,151
XS Rating Curve= 0 ,0
Exp/Cntr(USF)=0,0
Exp/Cntr=0.3,0.1