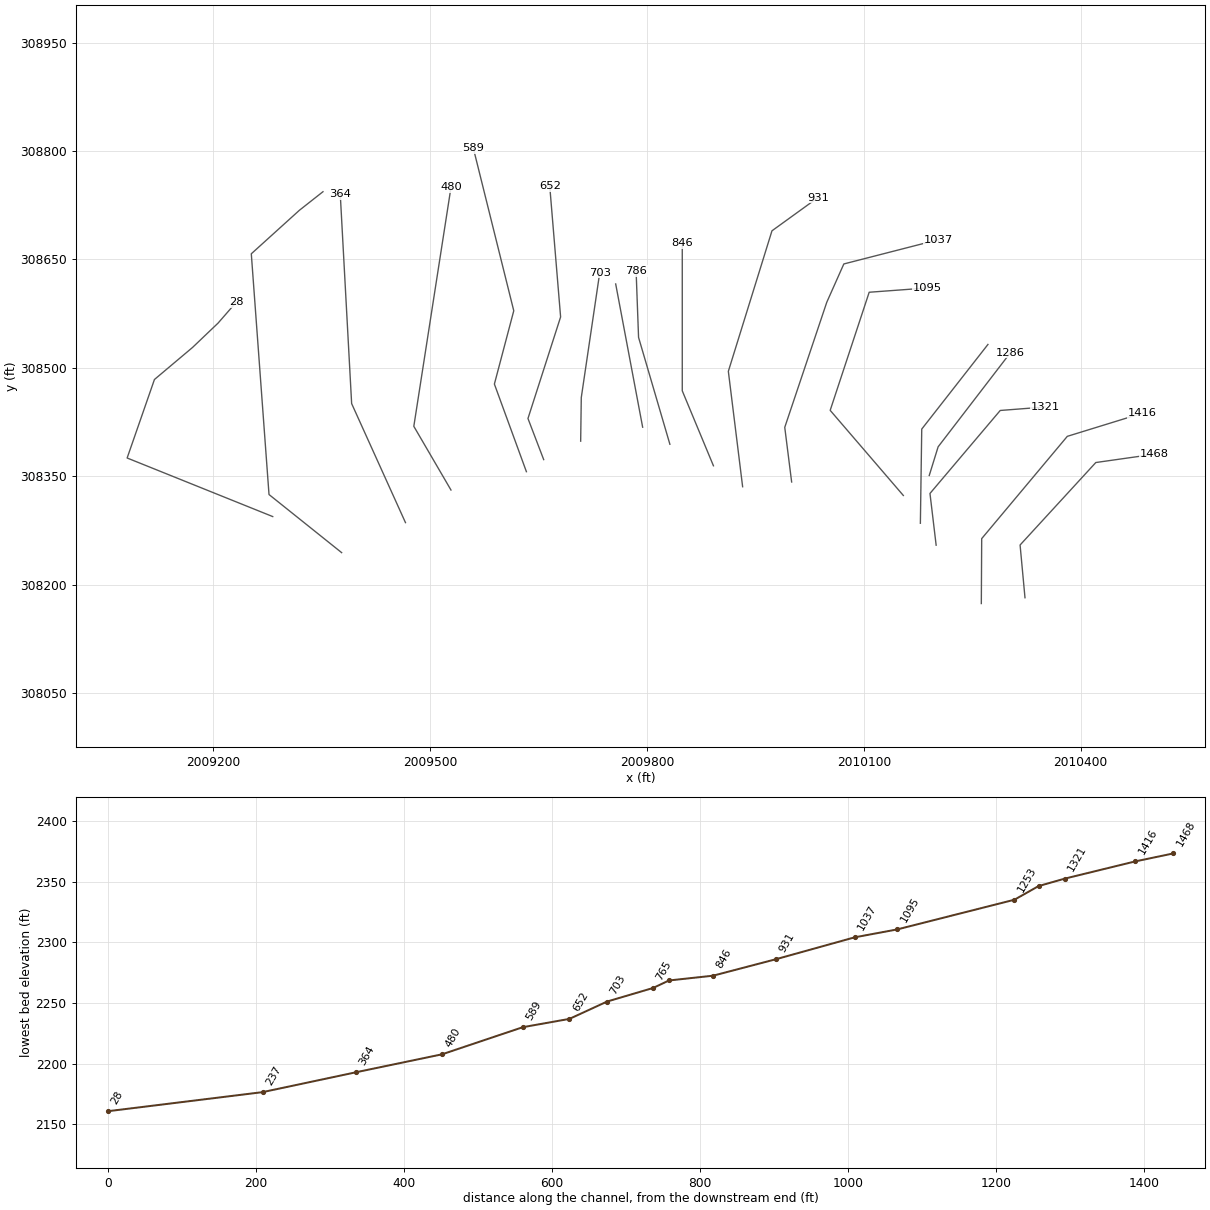
HEC-RAS study COONCK.prj: COONCK

--- COONCK.g01 (geometry) --- (continued)

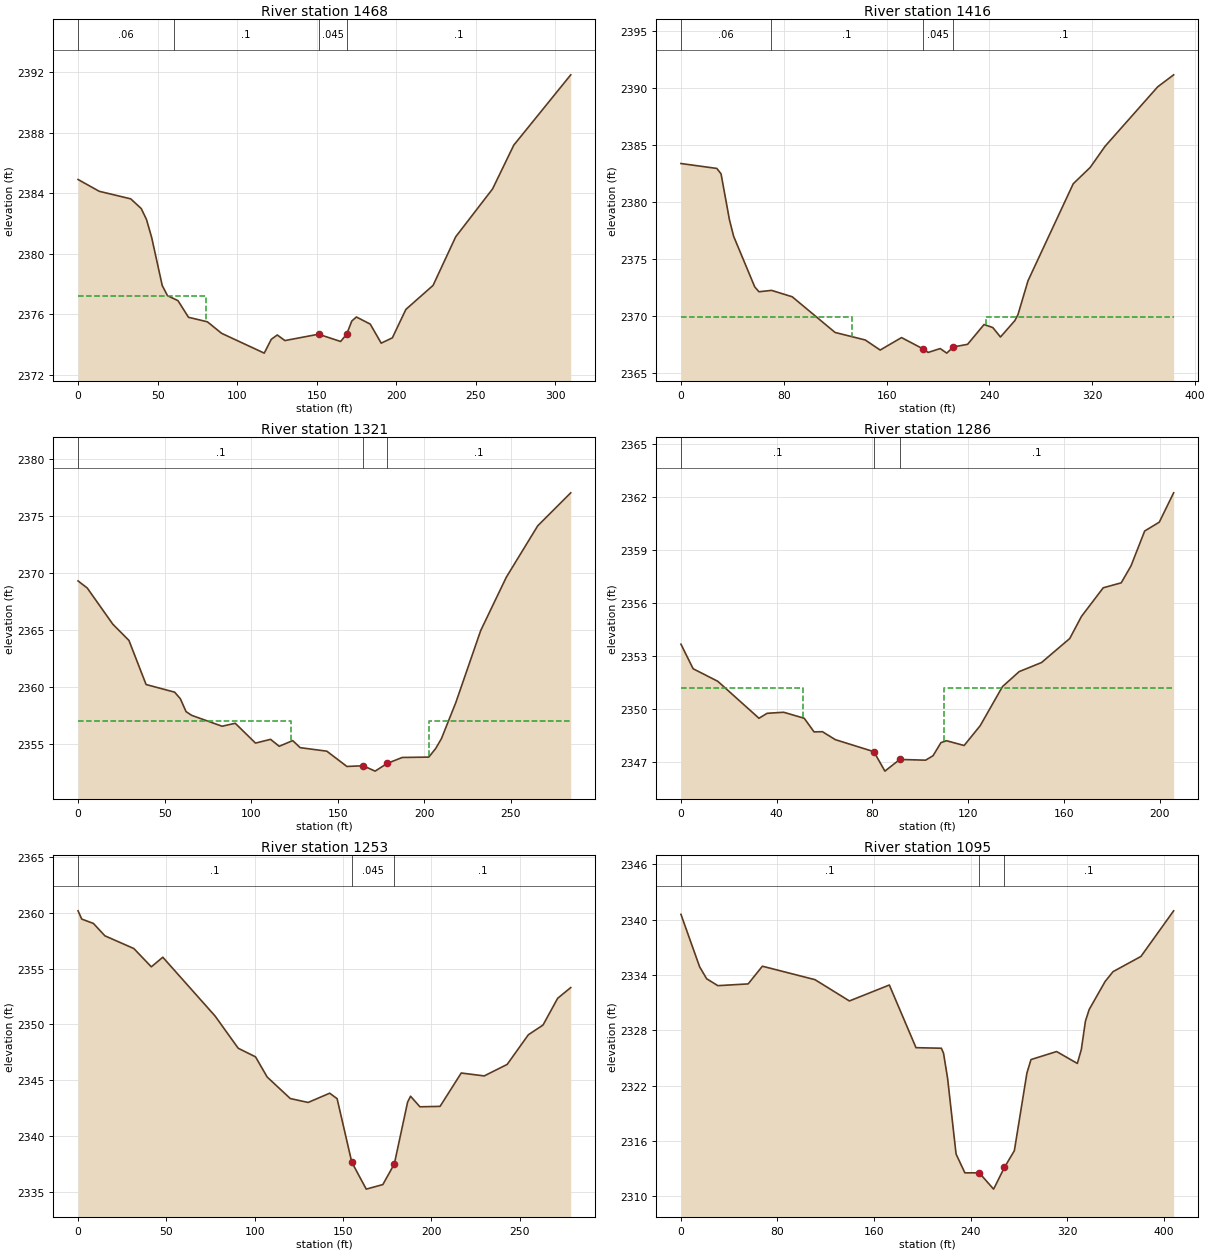
Type RM Length L Ch R = 1 ,1468    ,51.2,51.9,52
XS GIS Cut Line= 4
2010322.93482286308181.878414793 2010316.1476862308254.840133932
2010420.92410845308368.9488690982010501.52135634308380.402162219
#Sta/Elev= 30
       0  2384.9    13.3 2384.12    33.1 2383.62    39.7 2382.98      43 2382.26
    46.3 2381.05    52.9 2377.89    56.2 2377.22    62.8 2376.89    69.4 2375.79
    81.3 2375.49    90.2 2374.73     117 2373.42   121.4 2374.33   125.2 2374.62
     130 2374.25   151.1 2374.67     165 2374.19   168.8 2374.67     172 2375.54
   174.9 2375.81   183.6 2375.34   190.5 2374.08   197.5 2374.43     206 2376.31
   223.1  2377.9   237.3 2381.11   260.5 2384.28   273.8 2387.17   309.6 2391.82
#Mann= 4 ,-1 , 0
       0     .06       0      60      .1       0   151.1    .045       0
   168.8      .1       0
#XS Ineff= 2 , 0
           80.12 2377.19
Permanent Ineff=
       F       F
Bank Sta=151.1,168.8
XS Rating Curve= 0 ,0
Exp/Cntr(USF)=0,0
Exp/Cntr=0.3,0.1

Type RM Length L Ch R = 1 ,1416    ,94.6,95,95.5
XS GIS Cut Line= 4
2010262.52214719308173.8462717132010263.03300857 308263.66889898
2010381.47775604308405.173855192 2010485.5522106308437.257474415
#Sta/Elev= 30
       0 2383.37    27.9 2382.94    31.2 2382.47    37.7 2378.47      41    2377
    57.4 2372.58    60.7 2372.15    70.5 2372.27    86.6 2371.71   119.9 2368.59
   143.4 2367.93     155 2367.05   171.6 2368.14   188.7 2367.13   192.3 2366.84
   201.7 2367.18   206.8 2366.78   211.9 2367.32     223 2367.55   235.8 2369.28
   242.6 2369.02   248.6 2368.19   259.8 2369.63   262.2 2370.15     270 2373.11
   305.2  2381.6   318.4 2383.03   329.9 2384.87   370.9 2390.08   383.3 2391.13
#Mann= 4 ,-1 , 0
       0     .06       0      70      .1       0   188.7    .045       0
   211.9      .1       0
#XS Ineff= 2 , 0
             133  2369.9  237.07          2369.9
Permanent Ineff=
       F       F
Bank Sta=188.7,211.9
XS Rating Curve= 0 ,0
Exp/Cntr=0.3,0.1

Type RM Length L Ch R = 1 ,1321    ,34.9,35.2,35.7
XS GIS Cut Line= 4
 2010200.0159304308254.5901673792010191.47124183308326.151934121
2010288.66707427308440.9711867292010350.61606638308445.777574047
#Sta/Elev= 30
       0  2369.3     5.3 2368.68    20.1  2365.5    29.4 2364.08    39.3 2360.21
    55.8 2359.54    59.1 2358.96    62.4 2357.83    65.7  2357.5    83.2 2356.55
    90.8 2356.81   102.5 2355.07   111.2  2355.4   116.2 2354.79     124 2355.29
   128.3 2354.67   143.7 2354.36   155.3 2353.02   164.7 2353.08   171.6 2352.61
   178.6 2353.29   187.3 2353.81   202.6 2353.84   206.6  2354.6   209.9 2355.46
   218.2 2358.62   232.6 2364.95   247.4 2369.63   265.5 2374.13   284.6 2377.03
#Mann= 3 ,-1 , 0
       0      .1       0   164.7    .045       0   178.6      .1       0
#XS Ineff= 2 , 0
             123    2357     203            2357
Permanent Ineff=
       F       F
Bank Sta=164.7,178.6
XS Rating Curve= 0 ,0
Exp/Cntr=0.3,0.1

Type RM Length L Ch R = 1 ,1286    ,34.1,32.7,32.8
XS GIS Cut Line= 3
2010190.47146271308351.0163910462010202.74576029 308390.67181402
2010302.82849446 308520.96820379
#Sta/Elev= 30
       0 2353.68     5.1 2352.29    15.4 2351.58    32.6 2349.49      36 2349.77
    42.9 2349.83    51.5 2349.49    55.6 2348.72    59.1 2348.73    64.5 2348.28
    80.6  2347.6    85.2  2346.5    91.4 2347.16   102.2 2347.12   105.3 2347.37
   108.6 2348.11   110.9 2348.22   118.3 2347.95     125 2349.07   134.3 2351.28
   141.3 2352.13   150.6 2352.64   162.4    2354   167.3 2355.25   176.4 2356.87
   183.9 2357.15     188 2358.11   193.7 2360.08   199.8 2360.58   205.8 2362.24
#Mann= 3 ,-1 , 0
       0      .1       0    80.6    .045       0    91.4      .1       0
#XS Ineff= 2 , 0
              51  2351.2     110          2351.2
Permanent Ineff=
       F       F
Bank Sta=80.6,91.4
XS Rating Curve= 0 ,0
Exp/Cntr=0.3,0.1

Type RM Length L Ch R = 1 ,1253    ,151.2,158.3,161.2
XS GIS Cut Line= 3
2010178.19716512308284.9240194232010180.08551859308415.220409194
2010271.67066213 308532.29832464
#Sta/Elev= 30
       0 2360.18     2.1 2359.44     8.7 2359.05    15.2 2357.94    31.6  2356.8
    41.5 2355.16      48 2356.02    77.6 2350.75    90.7 2347.86   100.5 2347.09
   107.1 2345.28   120.2 2343.35   130.3    2343   142.5 2343.83   146.7 2343.34
     155 2337.65   163.2 2335.23   172.6 2335.64   179.1 2337.49   186.6 2343.02
   188.3 2343.56   193.6 2342.61     205 2342.65     217 2345.64     230 2345.38
     243 2346.41     255 2349.07   263.3 2349.94   271.6 2352.34     279  2353.3
#Mann= 3 ,-1 , 0
       0      .1       0     155    .045       0   179.1      .1       0
Bank Sta=155,179.1
XS Rating Curve= 0 ,0
Exp/Cntr=0.3,0.1

Type RM Length L Ch R = 1 ,1095    ,57.8,57.5,55
XS GIS Cut Line= 4
2010154.62763465308323.3378861152010053.41059879308441.134049844
2010107.36554627308604.5333802332010188.08149925 308610.49722708
#Sta/Elev= 30
       0 2340.58    15.5 2334.88    21.3 2333.59    30.6 2332.84    55.7 2333.03
    67.5 2334.95   111.1 2333.49   139.6 2331.18   172.7 2332.91   194.8 2326.11
   215.8 2326.05   217.6 2325.52     221 2322.77     228 2314.57   235.3 2312.53
   247.2 2312.53   259.1 2310.76   268.1 2313.12   276.3 2314.93   286.7 2323.35
   290.1 2324.82   311.3 2325.69   328.5  2324.4   331.8 2325.91   335.2 2328.98
   338.3 2330.25   351.5 2333.29   358.1 2334.36   381.2 2336.01   408.3 2340.96
#Mann= 3 ,-1 , 0
       0      .1       0   247.2    .045       0   268.1      .1       0
Bank Sta=247.2,268.1
XS Rating Curve= 0 ,0
Exp/Cntr=0.5,0.3

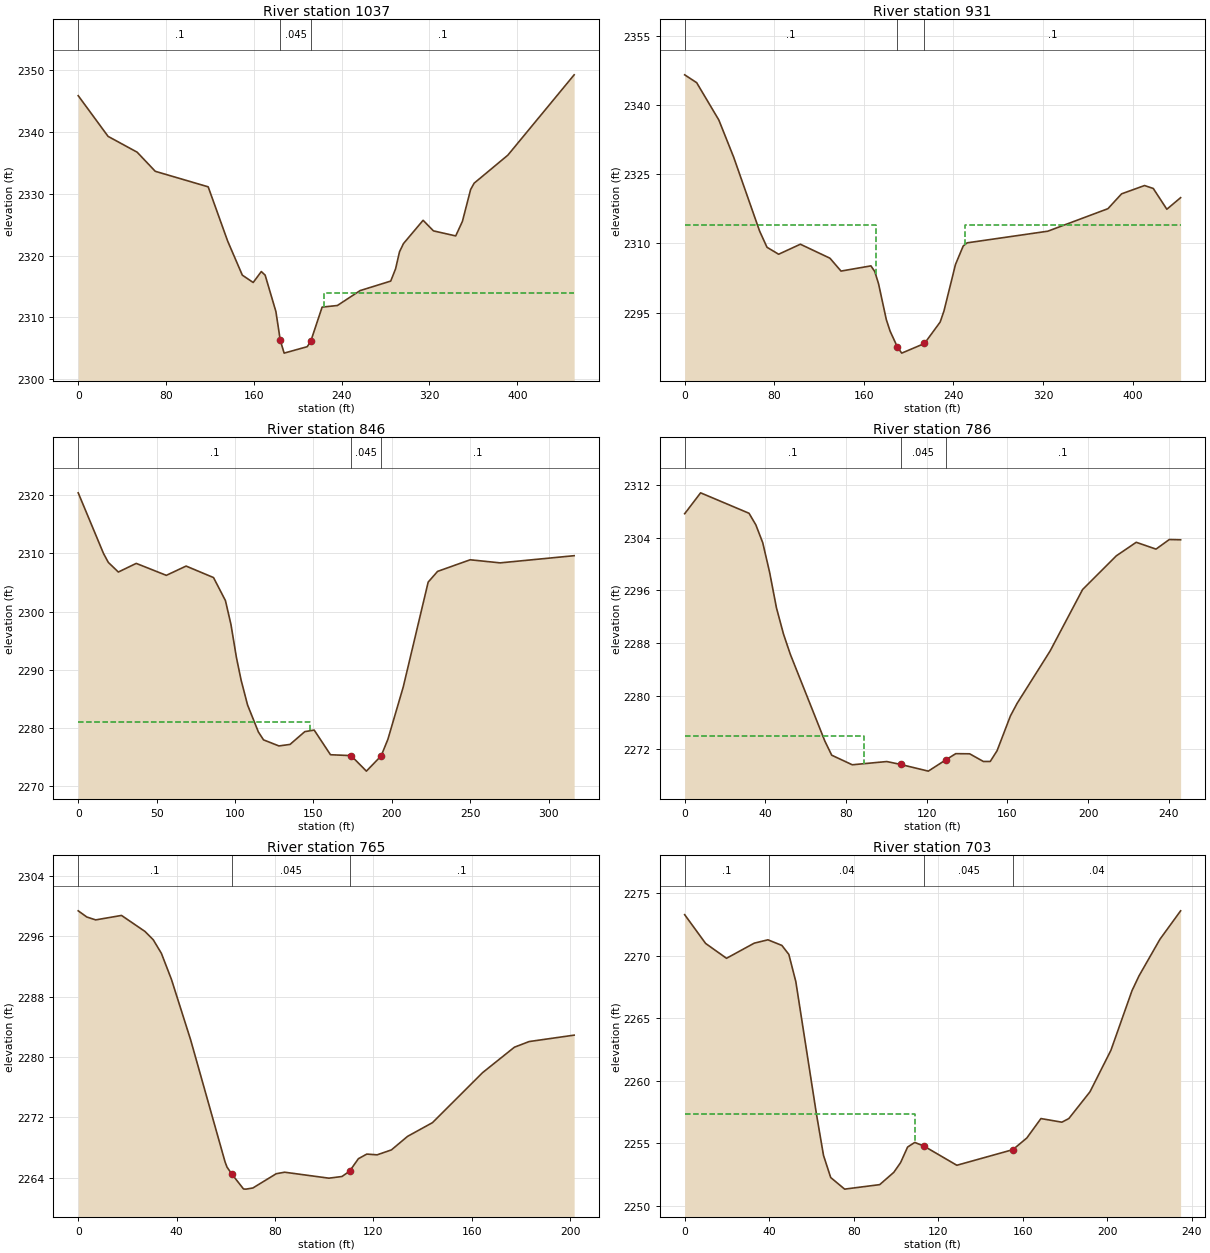
Type RM Length L Ch R = 1 ,1037    ,104.7,106.2,106.4
XS GIS Cut Line= 5
2010000.08786679308342.0361156122009990.55312974308417.607965202
2010048.67317188 308590.646039082010072.29786629308643.688398117
2010203.03470424308677.252606502
#Sta/Elev= 30
       0 2345.86    27.2 2339.28    53.7 2336.72    70.2 2333.63   118.4 2331.12
   136.1 2322.37   149.5 2316.84   159.4 2315.65   166.8 2317.42   170.3 2316.84
   180.1 2310.95   184.1 2306.28   187.6 2304.23   208.6 2305.27   211.8 2306.12
   222.2 2311.67   236.1 2311.93   256.8 2314.34   284.7 2315.88   289.1 2317.85
   292.7 2320.61   296.3 2321.94   314.2 2325.71   323.6    2324   343.9 2323.18
     350 2325.53   357.5 2330.69   360.7 2331.71   391.4 2336.24   451.8 2349.23
#Mann= 3 ,-1 , 0
       0      .1       0   184.1    .045       0   211.8      .1       0
#XS Ineff= 2 , 0
             172    2314     224            2314
Permanent Ineff=
       F       F
Bank Sta=184.1,211.8
XS Rating Curve= 0 ,0
Exp/Cntr=0.5,0.3

Type RM Length L Ch R = 1 ,931     ,77.3,84.9,85.8
XS GIS Cut Line= 4
 2009932.2748853 308335.465063862009912.51529299308495.143931438
2009972.86215599308689.535596315 2010036.4132772308735.463297358
#Sta/Elev= 30
       0 2346.52    10.7 2344.82    30.5 2336.73    43.8 2328.64    66.9 2312.66
    73.5 2309.15    83.9 2307.64   103.3 2309.81   129.7 2306.78   139.6 2303.99
   166.3 2305.12   169.7  2303.9   173.1 2301.25     180 2293.51   183.4 2290.98
     190 2287.49   193.8 2286.21   214.1  2288.3   228.1 2292.94   231.5 2295.34
   241.8 2305.43   248.7 2309.43   252.2 2310.11   324.2 2312.63   377.9 2317.51
   390.1 2320.73   410.6 2322.53   418.4 2321.89   430.5 2317.39   442.8  2319.9
#Mann= 3 ,-1 , 0
       0      .1       0     190    .045       0   214.1      .1       0
#XS Ineff= 2 , 0
             171    2314     250            2314
Permanent Ineff=
       F       F
Bank Sta=190,214.1
XS Rating Curve= 0 ,0
Exp/Cntr=0.5,0.3

Type RM Length L Ch R = 1 ,846     ,57.2,59.6,64.5
XS GIS Cut Line= 3
2009891.88982359308364.4301977252009848.76076275308468.173073819
2009848.76076275308672.161875128
#Sta/Elev= 30
       0 2320.35    16.1 2309.97    19.2 2308.42    25.6 2306.77      37 2308.25
    56.2  2306.2    68.8 2307.79    86.3 2305.82    93.9 2301.87    97.4  2297.8
   100.9 2292.12   103.9 2288.23     108 2283.98   114.9 2279.35   118.2 2277.99
     128 2276.95   135.1 2277.21   144.5  2279.4   150.5 2279.67   160.9 2275.44
     174 2275.29   183.8 2272.63   193.2 2275.24   197.5 2278.08   207.3 2287.06
   223.2 2305.04   229.2 2306.88     250 2308.87   269.1 2308.34   316.3 2309.57
#Mann= 3 ,-1 , 0
       0      .1       0     174    .045       0   193.2      .1       0
#XS Ineff= 2 , 0
          148.08 2281.01
Permanent Ineff=
       F       F
Bank Sta=174,193.2
XS Rating Curve= 0 ,0
Exp/Cntr=0.3,0.1

Type RM Length L Ch R = 1 ,786     ,26.6,21.4,23
XS GIS Cut Line= 3
2009831.62864114308394.2423060872009788.29092889308542.100383177
2009784.89189263308633.874362061
#Sta/Elev= 30
       0  2307.6     7.9 2310.76    31.9 2307.67    35.3 2305.91    38.7 2303.22
    42.1 2298.77    45.5 2293.38      49  2289.4    52.4 2286.33    69.5 2273.23
    72.9 2271.09    83.1 2269.64   100.2 2270.13   107.1 2269.69   120.8 2268.68
   129.4 2270.37   134.4 2271.32   141.3  2271.3   148.1 2270.14   151.5 2270.14
   154.9 2271.77   161.5 2277.02   164.8 2278.91   181.2 2286.85   197.3 2296.14
     214 2301.23   223.9 2303.28   233.7 2302.25   240.3  2303.7   245.9 2303.66
#Mann= 3 ,-1 , 0
       0      .1       0   107.1    .045       0   129.4      .1       0
#XS Ineff= 2 , 0
              89    2274
Permanent Ineff=
       F       F
Bank Sta=107.1,129.4
XS Rating Curve= 0 ,0
Exp/Cntr=0.3,0.1

Type RM Length L Ch R = 1 ,765     ,76,62.1,56.3
XS GIS Cut Line= 2
2009793.94052232308417.8538631092009756.63971294308616.014412947
#Sta/Elev= 30
       0 2299.36     3.5 2298.54     7.1 2298.16    17.6 2298.75    27.1 2296.64
    30.5 2295.53    33.8 2293.74    37.9 2290.28    45.7 2282.28    59.7 2266.11
    60.5 2265.42    62.5 2264.48    67.2 2262.53    68.2 2262.51      71 2262.66
    80.5 2264.55    83.9 2264.75   101.9 2263.96   107.2 2264.18   110.3 2264.88
   113.9 2266.54   117.3 2267.15   121.5 2267.05   127.3  2267.7   133.9  2269.5
     144 2271.31   164.4 2277.94   177.3  2281.3   183.3 2282.05   201.6  2282.9
#Mann= 3 ,-1 , 0
       0      .1       0    62.5    .045       0   110.3      .1       0
Bank Sta=62.5,110.3
XS Rating Curve= 0 ,0
Exp/Cntr=0.3,0.1

Type RM Length L Ch R = 1 ,703     ,54.1,50.9,49.5
XS GIS Cut Line= 3
2009708.19062416308398.5018664582009709.04038322308458.834759982
2009734.53315513308631.335849917
#Sta/Elev= 30
       0  2273.3     9.9    2271    19.8 2269.81    32.9 2271.02    39.4 2271.29
      46 2270.84    49.3 2270.12    52.6 2267.94    62.4  2257.3    65.7 2254.03
    69.1 2252.26    75.7 2251.33    92.3 2251.69      99 2252.68   102.2 2253.46
   105.5  2254.7   108.9 2255.07   113.4 2254.76   128.8 2253.24   155.3 2254.49
   161.9 2255.42   168.6 2256.98   178.5 2256.69   181.8 2256.98   191.8 2259.12
   201.7 2262.44   211.7 2267.22     215  2268.4   224.9 2271.33   234.7 2273.61
#Mann= 4 ,-1 , 0
       0      .1       0      40     .04       0   113.4    .045       0
   155.3     .04       0
#XS Ineff= 2 , 0
          109.17 2257.33
Permanent Ineff=
       F       F
Bank Sta=113.4,155.3
XS Rating Curve= 0 ,0
Exp/Cntr=0.5,0.3

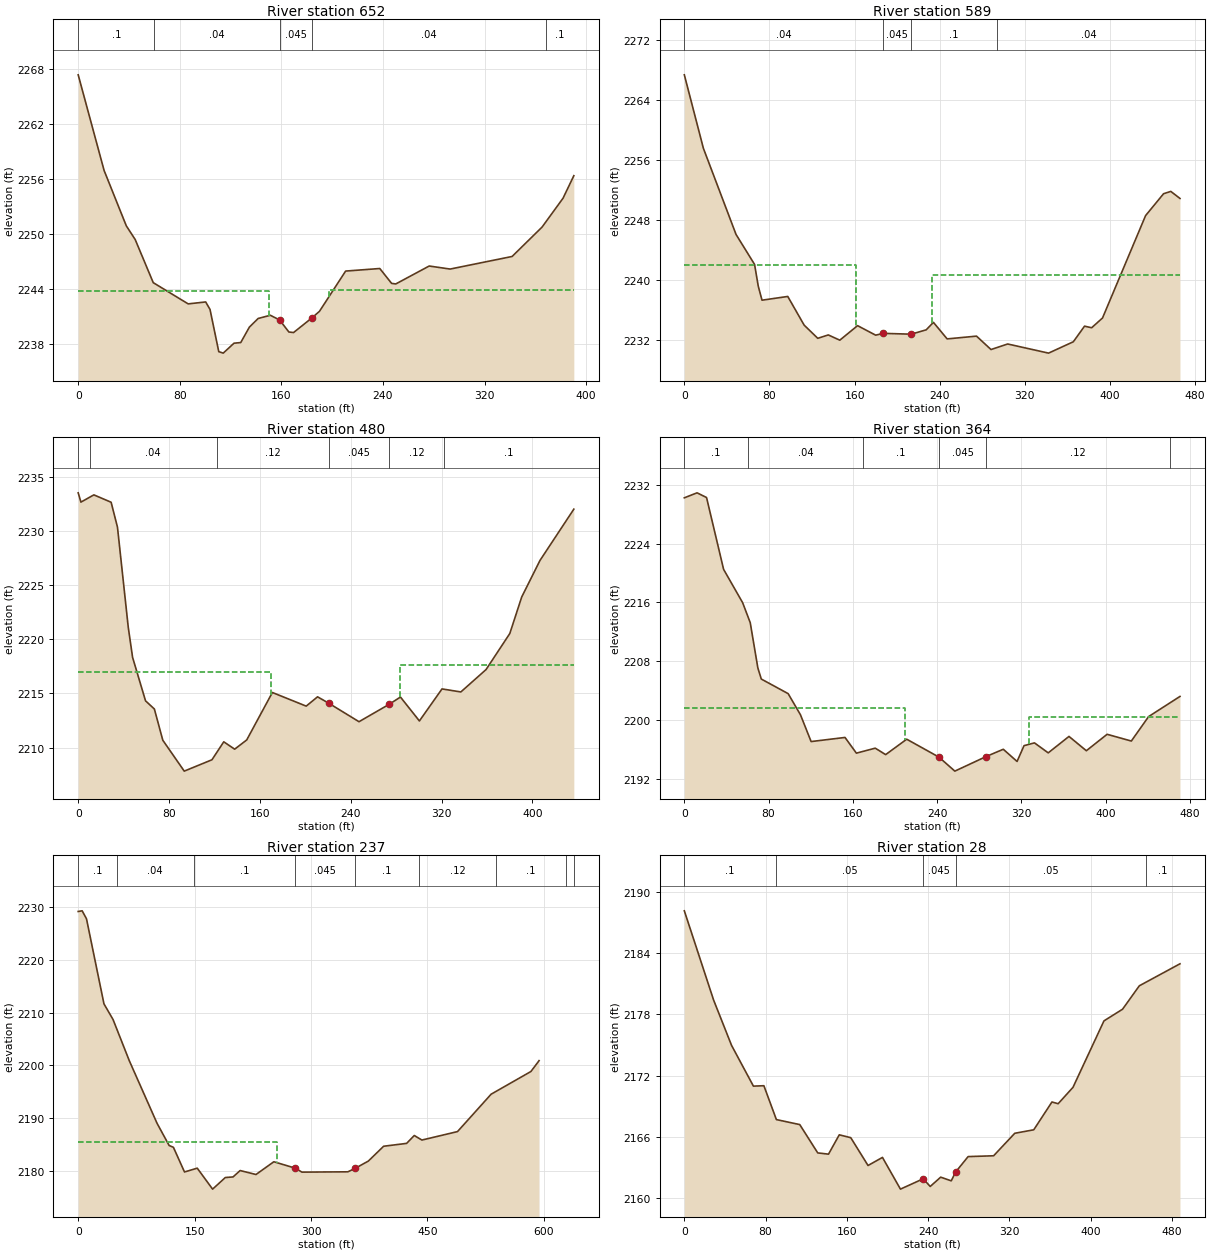
Type RM Length L Ch R = 1 ,652     ,62.2,63,64.2
XS GIS Cut Line= 4
2009657.02467648308372.9960082572009635.28112654308429.863754271
 2009680.4408072308570.3605385412009665.38758031308751.556788096
#Sta/Elev= 30
       0 2267.32    20.4 2256.91    37.9 2250.88    44.9 2249.39    59.1  2244.7
    86.6 2242.39   100.4  2242.6   103.8 2241.79   110.7 2237.19   114.2 2237.03
   122.7 2238.11     128 2238.18   134.8 2239.86   141.7  2240.8   151.3 2241.15
   158.6 2240.64   165.9 2239.33   169.6 2239.27     184 2240.86     190 2241.58
   210.6 2245.96   237.5 2246.24   246.8 2244.62   250.1 2244.56   276.4 2246.51
   292.9 2246.18   341.7 2247.55   365.3 2250.75   381.8 2253.89   390.3 2256.34
#Mann= 5 ,-1 , 0
       0      .1       0      60     .04       0   158.6    .045       0
     184     .04       0  368.46      .1       0
#XS Ineff= 2 , 0
          150.21  2243.8  197.41          2243.9
Permanent Ineff=
       F       F
Bank Sta=158.6,184
XS Rating Curve= 0 ,0
Exp/Cntr=0.5,0.3

Type RM Length L Ch R = 1 ,589     ,107.8,109.1,111.6
XS GIS Cut Line= 4
2009633.11545851308356.2706456732009588.82074736308477.498276165
2009615.63070411308578.9098516732009559.67949003308803.880358258
#Sta/Elev= 30
       0 2267.35    17.9 2257.54    48.6 2246.03      66 2242.03    69.5 2239.11
      73 2237.25    97.2 2237.75   112.6 2233.92   125.4 2232.16   135.3 2232.61
   146.1 2231.91   162.8 2233.85   179.8 2232.58     187 2232.82   213.2 2232.71
   227.3 2233.29   234.1 2234.29     247 2232.08   274.6 2232.45   288.2 2230.66
   303.9  2231.4   342.3 2230.18   365.6  2231.7   376.1 2233.78   382.8 2233.57
     393 2234.87   433.5 2248.55   450.4 2251.47   457.2 2251.78   465.8 2250.84
#Mann= 4 ,-1 , 0
       0     .04       0     187    .045       0   213.2      .1       0
  293.96     .04       0
#XS Ineff= 2 , 0
          161.72  2241.9  233.14          2240.6
Permanent Ineff=
       F       F
Bank Sta=187,213.2
XS Rating Curve= 0 ,0
Exp/Cntr=0.5,0.3

Type RM Length L Ch R = 1 ,480     ,109.9,116.3,124.8
XS GIS Cut Line= 3
2009528.75508063308330.909302908 2009477.3499027308419.032465072
2009528.75508063308749.494323185
#Sta/Elev= 30
       0 2233.55     2.4 2232.69    13.8 2233.36      29 2232.68    34.6 2230.37
    44.1 2221.11    47.9 2218.34    59.3 2214.32    67.1 2213.56    74.5 2210.68
    93.4 2207.82   117.8 2208.87   128.2 2210.53   137.8 2209.85   148.4  2210.7
     171 2215.09   200.8 2213.83   210.8 2214.69   220.8 2214.09   247.3 2212.39
   273.9    2214   283.8 2214.67   300.5 2212.46   320.4 2215.42     337 2215.14
   359.2 2217.21   380.1 2220.54   390.6 2223.92   406.7  2227.3   436.5 2232.04
#Mann= 6 ,-1 , 0
       0      .1       0      10     .04       0  122.02     .12       0
   220.8    .045       0   273.9     .12       0  322.02      .1       0
#XS Ineff= 2 , 0
          169.53 2216.99   283.8          2217.6
Permanent Ineff=
       F       F
Bank Sta=220.8,273.9
XS Rating Curve= 0 ,0
Exp/Cntr=0.3,0.1

Type RM Length L Ch R = 1 ,364     ,129.1,126.1,125.8
XS GIS Cut Line= 3
 2009465.8099648308285.7986365622009391.32491106308450.505022987
2009375.58863211 308740.05255581
#Sta/Elev= 30
       0 2230.26    12.1 2230.94    21.1  2230.3    37.3 2220.51    55.4 2215.96
    62.6 2213.24    69.8 2207.09    73.1 2205.56    98.6 2203.57   110.3 2200.69
   120.4 2197.04   152.6  2197.6   163.4 2195.46   181.3 2196.14   191.2 2195.26
   211.2 2197.36   241.8 2194.92   256.9 2193.01   286.5 2194.99   302.9 2195.99
     316 2194.33   322.6 2196.48   332.5 2196.86   345.6  2195.5   365.3 2197.74
   381.8 2195.79   401.5 2198.03   424.5 2197.11   440.9 2200.44   470.7 2203.19
#Mann= 6 ,-1 , 0
       0      .1       0      60     .04       0     170      .1       0
   241.8    .045       0   286.5     .12       0  460.77      .1       0
#XS Ineff= 2 , 0
          209.76 2201.68  327.79         2200.35
Permanent Ineff=
       F       F
Bank Sta=241.8,286.5
XS Rating Curve= 0 ,0
Exp/Cntr=0.3,0.1

Type RM Length L Ch R = 1 ,237     ,201.4,209,171
XS GIS Cut Line= 5
2009377.49424523308244.2779929122009277.00462636308324.669688003
2009252.50002357308657.7517507732009319.08395835308717.982872783
2009351.66121791308743.631004402
#Sta/Elev= 30
       0 2229.09     5.1 2229.21    10.7  2227.7    33.2 2211.64    44.9 2208.68
    65.9 2200.88   101.7 2189.05   117.2 2184.88   122.7 2184.54     137 2179.88
   153.4  2180.6   173.2 2176.64   189.6 2178.83   199.5 2178.94   208.7 2180.15
   229.1  2179.4   252.1 2181.81   279.72180.604   288.3 2179.85   347.5 2179.91
   357.12180.579   373.9 2181.94   393.6 2184.74   423.2 2185.28   433.1 2186.77
   442.9 2185.91   488.8 2187.51   532.1 2194.57   583.4 2198.86   593.9 2200.91
#Mann= 9 ,-1 , 0
       0      .1       0      50     .04       0  148.69      .1       0
   279.7    .045       0   357.1      .1       0  438.69     .12       0
  538.69      .1       0  628.69     .12       0  638.69      .1       0
#XS Ineff= 2 , 0
          255.79 2185.61
Permanent Ineff=
       F       F
Bank Sta=279.7,357.1
XS Rating Curve= 0 ,0
Exp/Cntr=0.3,0.1

Type RM Length L Ch R = 1 ,28      ,,,
XS GIS Cut Line= 6
2009282.13091756308294.1818041822009080.71395821308375.220211105
2009118.48102771308483.800535914  2009171.146168308528.120627932
2009206.52263492308561.8571147962009231.48596769308590.503373289
#Sta/Elev= 30
       0 2188.12    28.8  2179.4    46.5 2174.96      68 2170.98    78.3 2171.02
    90.6 2167.71   113.6 2167.22   131.3 2164.45   141.9 2164.33   152.5 2166.22
   163.8 2165.94   180.8 2163.22     195 2164.01   212.7 2160.91   235.1 2161.92
     242 2161.17   252.3 2162.08   262.7 2161.72     267 2162.58   279.3 2164.09
   304.4 2164.17   325.2 2166.37   343.9 2166.71   361.8 2169.43   367.9 2169.26
   382.5 2170.86     413 2177.36   431.3  2178.5   447.8 2180.79   487.8 2182.94
#Mann= 5 ,-1 , 0
       0      .1       0    90.1     .05       0   235.1    .045       0
     267     .05       0   454.5      .1       0
Bank Sta=235.1,267
XS Rating Curve= 0 ,0
Exp/Cntr=0.3,0.1
LCMann Table=0

Chan Stop Cuts=-1
Use User Specified Reach Order=0
Composite Channel Slope=5